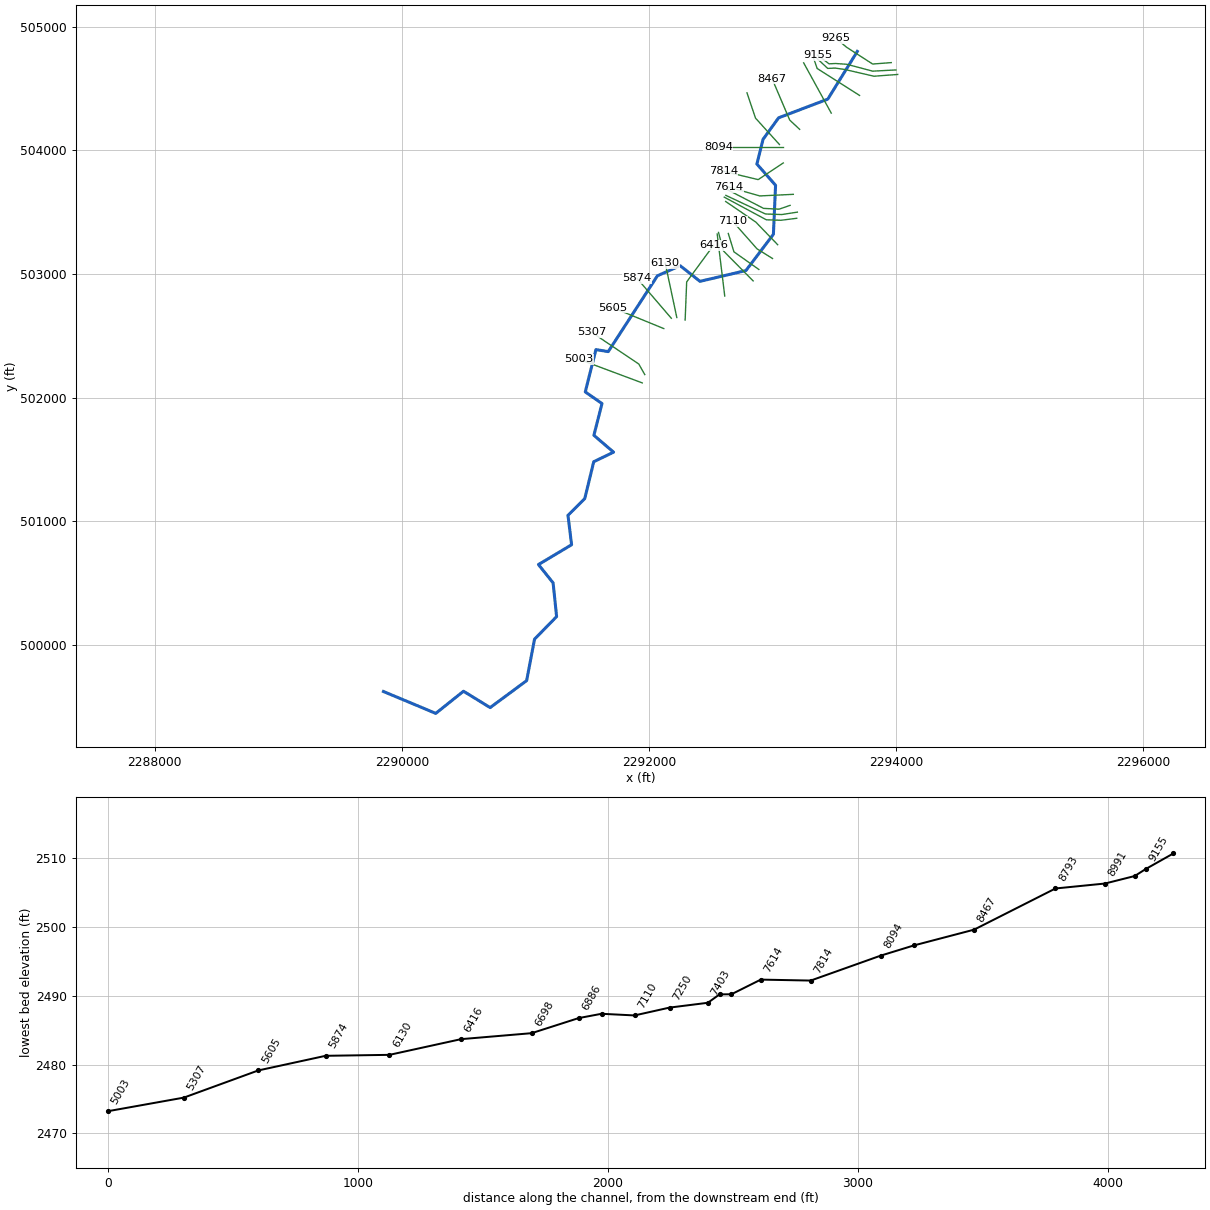
--- MOORERN1.prj (project) ---

Proj Title=MOORERN1
Current Plan=p01
Default Exp/Contr=0,0
English Units
Geom File=g01
Flow File=f01
Plan File=p01
Background Map Layer=Inundation Boundary (01pct Value_0)
BEGIN DESCRIPTION:
----------MODEL BY WOOD PLC 2021----------
Stream Name: Moore Run 1
Flood Zone: Approximate
Pocahontas County, WV
HEC-RAS Version: RAS 6.0
Vertical Datum: NAVD88
Projection: NAD 1983 StatePlane West Virginia S FIPS 4702 (US Feet)
Terrain: 1-meter LIDAR (FEMA Region III 3DEP collected 2016-2018)
Land Use: 2019 NLCD
Hydrologic Method:
WV SIR2010-5033 regression equations
Model Notes:
END DESCRIPTION:
DSS Export Rating Curves= 0
DSS Export Rating Curve Sorted= 0
DSS Export Volume Flow Curves= 0
DXF OffsetX= 0
DXF OffsetY= 0
DXF ScaleX= 0
DXF ScaleY= 0

--- MOORERN1.p01 (plan) ---

Plan Title=Floodplain
Program Version=6.00
Short Identifier=Floodplain
Geom File=g01
Flow File=f01
Subcritical Flow
K Sum by GR= 0
Std Step Tol= 0.01
Critical Tol= 0.01
Num of Std Step Trials= 20
Max Error Tol= 0.3
Flow Tol Ratio= 0.001
Split Flow NTrial= 30
Split Flow Tol= 0.02
Split Flow Ratio= 0.02
Log Output Level= 0
Friction Slope Method= 1
Unsteady Friction Slope Method= 2
Unsteady Bridges Friction Slope Method= 1
Parabolic Critical Depth
Global Vel Dist= 0 , 0 , 0
Global Log Level= 0
CheckData=True
Encroach Param=-1 ,0,0, 0
Mapping Interval=1HOUR
Computation Time Step Use Courant=        0
Computation Time Step Use Time Series=    0
Computation Time Step Count To Double=0
Computation Time Step Max Doubling=0
Computation Time Step Max Halving=0
Computation Time Step Residence Courant=0
Run HTab= 0
Run UNet= 0
Run Sediment= 0
Run PostProcess= 0
Run WQNet= 0
Run RASMapper=-1
UNET Theta= 0
UNET Theta Warmup= 0
UNET ZTol= 0
UNET ZSATol= 0
UNET MxIter= 0
UNET Max Iter WO Improvement= 0
UNET MaxInSteps= 0
UNET DtIC= 0
UNET DtMin= 0
UNET MaxCRTS= 0
UNET WFStab= 0
UNET SFStab= 0
UNET WFX= 1
UNET SFX= 1
UNET Gravity=32.174
UNET 1D Methodology=Finite Difference
UNET DSS MLevel= 1
UNET Pardiso=0
UNET DZMax Abort= 0
UNET Use Existing IB Tables= 0
UNET Froude Reduction=False
UNET Froude Limit= 0
UNET Froude Power= 0
UNET D1 Cores= 0
UNET WindReference=Eulerian
UNET WindDragFormulation=Hsu (1988)
UNET D2 Coriolis=0
UNET D2 Cores= 0
UNET D2 Theta= 1
UNET D2 Theta Warmup= 1
UNET D2 Z Tol= 0.01
UNET D2 Volume Tol= 0.01
UNET D2 Max Iterations= 20
UNET D2 Equation= 0
UNET D2 RampUpFraction=0.1
UNET D2 TimeSlices= 1
UNET D2 Turbulence Formulation=Non-Conservative (original)
UNET D2 Eddy Viscosity=0.3
UNET D2 Transverse Eddy Viscosity=0.1
UNET D2 Smagorinsky Mixing=0
UNET D2 BCVolumeCheck=0
UNET D2 Cores=0
UNET D2 SolverType=PARDISO (Direct)
UNET D2 Minimum Iterations= 2147483647
UNET D2 Maximum Iterations= 2147483647
UNET D2 Restart Number= 10
UNET D2 Relaxation Coeff=1.3
UNET D2 SOR Precondition Iterations= 10
UNET D2 ILUT Maximum Fill= 8
UNET D2 ILUT Tolerance=1E-08
UNET D1D2 MaxIter= 0
UNET D1D2 ZTol=0.01
UNET D1D2 QTol=0.1
UNET D1D2 MinQTol=1
Write IC File= 0
Write IC File at Fixed DateTime=0
Write IC File at Sim End=0
Echo Input=False
Echo Parameters=False
Echo Output=False
Write Detailed= 0
HDF Write Warmup=0
HDF Write Time Slices=0
HDF Flush=0
HDF Compression= 1
HDF Chunk Size= 1
HDF Spatial Parts= 1
HDF Use Max Rows=0
HDF Fixed Rows= 1
Calibration Method= 0
Calibration Iterations= 20
Calibration Max Change=0.05
Calibration Tolerance=0.2
Calibration Maximum=1.5
Calibration Minimum=0.5
Calibration Optimization Method= 1
WQ AD Non Conservative
WQ ULTIMATE=-1
WQ Max Comp Step=1HOUR
WQ Output Interval=15MIN
WQ Output Selected Increments= 0
WQ Output face flow=0
WQ Output face velocity=0
WQ Output face area=0
WQ Output face dispersion=0
WQ Output cell volume=0
WQ Output cell surface area=0
WQ Output cell continuity=0
WQ Output cumulative cell continuity=0
WQ Output face conc=0
WQ Output face dconc_dx=0
WQ Output face courant=0
WQ Output face peclet=0
WQ Output face adv mass=0
WQ Output face disp mass=0
WQ Output cell mass=0
WQ Output cell source sink temp=0
WQ Output nsm pathways=0
WQ Output nsm derived pathways=0
WQ Create Restart=0
WQ Fixed Restart=0
WQ System Summary=0
WQ Write To DSS=0
Sorting and Armoring Iterations= 10
XS Update Threshold= 0.02
Bed Roughness Predictor= 0
Hydraulics Update Threshold= 0.02
Energy Slope Method= 1
Volume Change Method= 1
Sediment Retention Method= 0
Sediment TS Multiplier= 1
Warm Up Method= 0
XS Weighting Method= 0
Number of US Weighted Cross Sections= 1
Number of DS Weighted Cross Sections= 1
Upstream XS Weight=0
Main XS Weight=1
Downstream XS Weight=0
Number of DS XS's Weighted with US Boundary= 1
Upstream Boundary Weight= 1
Weight of XSs Associated with US Boundary= 0
Number of US XS's Weighted with DS Boundary= 1
Downstream Boundary Weight= 0.5
Weight of XSs Associated with DS Boundary= 0.5
Percentile Method= 0
Sediment Output Level= 3
Mass or Volume Output= 0
Output Increment Type= 1
Profile and TS Output Increment= 1
Transport Output Increment 1
XS Output Flag= 0
XS Output Increment= 10
Read HDF5 Sediment Hotstart= 0
Sediment Hotstart Type= 0
Write Gradation File= 0
Read Gradation Hotstart= 0
Write HDF5 File= 1
Write Binary Output= 1
Write DSS Sediment File= 0
DSS Sediment Output Type= 1
SV Curve= 0
Specific Gage Flag= 0
Subcell Erosion Methods= 0
Subcell Deposition Methods= 0
Advection Scheme= 1
Matrix Solver= 0
Implicit Weighting Factor= 1
Maximum Outer Loop Convergence Iterations= 5
Convergence Maximum Absolute= 0.001
Convergence RMSE= 0.0001
Grain Fractions Max Abs Error= 0.001
Max Subgrid Regions= 1
Max Subgrid Length Scale= 3.402823E+38
Initial Layer Thickness= 3.402823E+38
Min Layer Thickness= 3.402823E+38
Max Layer Thickness= 3.402823E+38
Number of Layers= 5

--- MOORERN1.f01 (steady flow) ---

Flow Title=Flow
Program Version=6.00
Number of Profiles= 6
Profile Names=01pct,10pct,04pct,02pct,0_2pct,01plus
River Rch & RM=MOORERN1,Main            ,9265
     622     330     438     527     867     920
River Rch & RM=MOORERN1,Main            ,7250
     737     393     521     625    1020    1090
River Rch & RM=MOORERN1,Main            ,5003
     914     492     649     777    1270    1350
River Rch & RM=MOORERN1,Main            ,3428
    1030     554     729     873    1420    1520
Boundary for River Rch & Prof#=MOORERN1,Main            , 1
Up Type= 0
Dn Type= 3
Dn Slope=0.00701
Boundary for River Rch & Prof#=MOORERN1,Main            , 2
Up Type= 0
Dn Type= 3
Dn Slope=0.00701
Boundary for River Rch & Prof#=MOORERN1,Main            , 3
Up Type= 0
Dn Type= 3
Dn Slope=0.00701
Boundary for River Rch & Prof#=MOORERN1,Main            , 4
Up Type= 0
Dn Type= 3
Dn Slope=0.00701
Boundary for River Rch & Prof#=MOORERN1,Main            , 5
Up Type= 0
Dn Type= 3
Dn Slope=0.00701
Boundary for River Rch & Prof#=MOORERN1,Main            , 6
Up Type= 0
Dn Type= 3
Dn Slope=0.00701
DSS Import GetInterval= 0
DSS Import GetPeak= 0
DSS Import FillOption= 0

--- MOORERN1.g01 (geometry) ---

Geom Title=Geometry
Program Version=6.00

River Reach=MOORERN1        ,Main
Reach XY= 30
2293684.73099999504801.2790000142293445.89099999      504414.956
2293047.75500004504263.6950000082292922.06900002504090.136999995
2292872.12199999503889.5360000132293023.20200004503717.906000003
2293005.67254917503321.2207696442292783.43000002503027.810000017
2292411.49699999502940.4130000032292251.39200003503066.780000001
2292067.35500003502985.6650000212291669.22100003502371.805000022
      2291569.45502388.1280000062291483.29600002 502045.63000001
     2291618.594501951.7000000032291553.05108424501694.582129389
2291712.24089478501558.1232958592291551.90648724501480.771272227
2291479.10606681501182.4857807462291343.40700002501047.215000004
2291372.51900004500808.834999993     2291104.455500648.644999996
 2291223.0233195500500.2185361092291251.32609905500227.515728459
2291072.72952394500044.8991596852291008.82600002      499709.316
      2290713.48 499491.027000012290498.12100001499623.518999994
2290273.36000003499444.3510000112289850.07000001499621.427000016

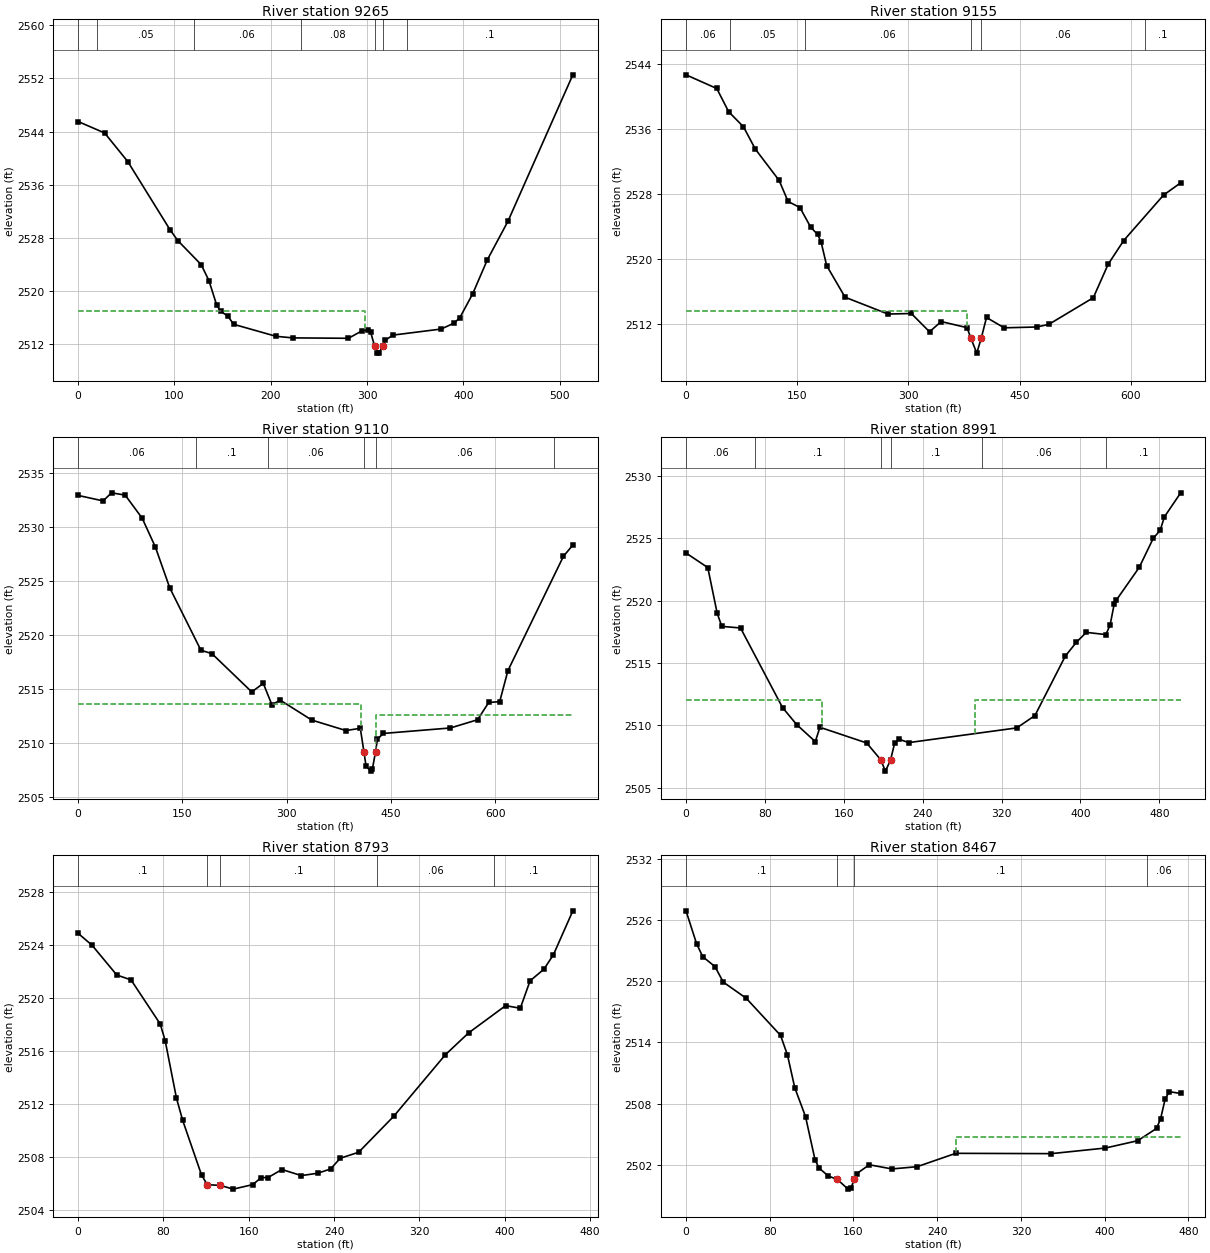
Type RM Length L Ch R = 1 ,9265    ,110.4,110.4,110.4
BEGIN DESCRIPTION:
structure xs 4
END DESCRIPTION:
XS GIS Cut Line= 4
2293959.59404116504710.510516975 2293808.8632406504698.905733263
2293597.68255278504834.8818014262293512.70358495504906.891084095
#Sta/Elev= 30
       0  2545.5    27.5 2543.78    51.6 2539.47    95.7 2529.17   103.7 2527.58
   127.8 2523.99   135.8  2521.6   143.8 2517.95   147.9 2516.98   155.4 2516.28
   161.5 2515.03   205.4 2513.23   222.8 2512.99   280.7 2512.93   295.1 2514.08
   300.9 2514.14   303.8 2513.82   307.82511.773   310.5  2510.7   312.5 2510.71
   316.22511.804   318.5  2512.6     327 2513.41     377 2514.32   390.6 2515.23
   396.4 2516.04   409.6 2519.58   424.9 2524.72   446.3 2530.51   513.7 2552.52
#Mann= 7 ,-1,0
       0     .06       0      20     .05       0     120     .06       0
  231.18     .08       0   307.8    .045       0   316.2     .08       0
  341.18      .1       0
#XS Ineff= 2 , 0
           297.8 2517.04
Permanent Ineff=
       F       F
Bank Sta=307.8,316.2
XS Rating Curve= 0 ,0
Exp/Cntr=0.5,0.3

Type RM Length L Ch R = 1 ,9155    ,44.1,44.6,45
BEGIN DESCRIPTION:
structure xs 3
END DESCRIPTION:
XS GIS Cut Line= 6
2293997.58018008504651.065242936 2293808.6328871 504641.44610802
2293599.07316215504697.0996743172293507.69138045504703.283403906
2293456.16030055504700.5350796442293362.03019459 504771.30442938
#Sta/Elev= 30
       0 2542.64    41.5 2540.96    57.5 2538.11    77.5 2536.25    93.5 2533.51
   125.6 2529.66   137.6 2527.08   153.6 2526.33   168.3 2523.89   177.6 2523.02
   182.3 2522.04   189.7 2519.19   214.5 2515.31   272.4 2513.24   303.8 2513.31
   328.4 2511.06     344 2512.32     379 2511.57   384.2 2510.25   392.1 2508.44
  398.13 2510.29   405.2 2512.82     429 2511.55   472.6 2511.65   489.1 2511.97
   549.2 2515.25   569.2 2519.36   590.2 2522.28   643.9 2527.86     667 2529.37
#Mann= 6 ,-1,0
       0     .06       0      60     .05       0     160     .06       0
   384.2    .045       0  398.13     .06       0  619.21      .1       0
#XS Ineff= 2 , 0
           378.5  2513.6   405.5          2512.6
Permanent Ineff=
       F       F
Bank Sta=384.2,398.13
XS Rating Curve= 0 ,0
Exp/Cntr(USF)=0,0
Exp/Cntr=0.5,0.3

Type RM Length L Ch R = 1 ,9110    ,123.5,118.9,114.2
BEGIN DESCRIPTION:
structure xs 2
END DESCRIPTION:
XS GIS Cut Line= 6
2294012.00888246 504614.649946472293819.62618414504600.221244097
2293579.14781126504655.8748103942293504.94305619504666.181026375
 2293445.1670035504663.4327021132293344.85316796504756.875727007
#Sta/Elev= 30
       0 2532.96    35.9 2532.45      48  2533.2    67.6 2532.99    92.1 2530.85
     111 2528.19   131.8 2524.39   176.6 2518.61   192.4  2518.3   249.7 2514.75
   266.3 2515.54   278.6 2513.58   290.9 2513.98   336.1 2512.14   385.3 2511.17
   405.9 2511.38  411.082509.197   414.1 2507.89   420.6 2507.41   423.3 2507.62
   427.8 2509.21   430.5 2510.35   438.7  2510.9   535.5 2511.41   574.5 2512.17
   590.6 2513.77   606.4 2513.85   618.2 2516.72   698.1 2527.32   711.6 2528.36
#Mann= 6 ,-1,0
       0     .06       0     170      .1       0  272.92     .06       0
  411.08    .045       0   427.8     .06       0  684.51      .1       0
#XS Ineff= 2 , 0
           406.5  2513.6   427.8          2512.6
Permanent Ineff=
       F       F
Bank Sta=411.08,427.8
XS Rating Curve= 0 ,0
Exp/Cntr(USF)=0,0
Exp/Cntr=0.5,0.3

Type RM Length L Ch R = 1 ,8991    ,202.6,198,192.6
XS GIS Cut Line= 3
2293702.82240303504444.9409233172293359.96895139504662.745621048
2293328.36322239504752.753240615
#Sta/Elev= 30
       0 2523.83    22.1 2522.66    31.6    2519    36.3 2517.94    55.3 2517.81
    97.9 2511.42   112.3 2510.05   131.1 2508.69   135.8 2509.84   183.2 2508.58
   197.4 2507.24   202.2 2506.32   207.42507.203   211.6 2508.59   216.4 2508.87
   225.9 2508.61   335.4 2509.79   353.8 2510.78   384.6 2515.55   395.8 2516.66
   405.9 2517.46   425.7 2517.28     430 2518.04   434.2 2519.73   436.2 2520.03
   459.6 2522.68   473.8 2525.01   480.8 2525.65   485.1 2526.73   501.6 2528.66
#Mann= 6 ,-1,0
       0     .06       0      70      .1       0   197.4    .045       0
   207.4      .1       0     300     .06       0  426.19      .1       0
#XS Ineff= 2 , 0
          138.21    2512  292.84            2512
Permanent Ineff=
       F       F
Bank Sta=197.4,207.4
XS Rating Curve= 0 ,0
Exp/Cntr(USF)=0,0
Exp/Cntr=0.3,0.1

Type RM Length L Ch R = 1 ,8793    ,326.8,325.7,324.1
XS GIS Cut Line= 2
2293473.79772272504301.6753235322293250.61274124504708.394411892
#Sta/Elev= 30
       0 2524.89    13.1 2523.99    36.2 2521.75    49.6 2521.38      77 2518.05
    81.6  2516.8    92.2 2512.46      98 2510.79   115.7 2506.67  121.032505.936
   133.4 2505.88   145.4  2505.6   163.7 2505.94   171.7 2506.47     178 2506.47
   191.1 2507.08   209.3 2506.62   224.7  2506.8   236.7 2507.12   245.8 2507.93
     263 2508.38     296  2511.1   344.3 2515.73   366.1 2517.38   400.9 2519.44
   414.6 2519.24   423.8 2521.31   436.8 2522.19   445.7 2523.28   463.9 2526.59
#Mann= 5 ,-1,0
       0      .1       0  121.03    .045       0   133.4      .1       0
     280     .06       0     390      .1       0
Bank Sta=121.03,133.4
XS Rating Curve= 0 ,0
Exp/Cntr=0.3,0.1

Type RM Length L Ch R = 1 ,8467    ,235.4,241.4,241.8
XS GIS Cut Line= 3
2293218.19169625504170.2943577712293137.73237891504245.373241364
2292995.44708358504578.888979262
#Sta/Elev= 30
       0  2526.9    10.1 2523.68      16  2522.4    27.7 2521.43    35.6 2519.91
    57.5 2518.33    90.3 2514.69    96.9 2512.78   103.9 2509.56   114.2 2506.72
   123.3 2502.47   127.2 2501.67   135.9  2500.9   144.6 2500.56   154.8 2499.61
   157.7 2499.74  160.822500.616   162.9 2501.11   175.1    2502   196.8 2501.59
   220.8 2501.81   257.7 2503.12     349 2503.09   400.7 2503.64   431.6 2504.36
   449.5 2505.56   453.4 2506.51   457.7 2508.41   461.6 2509.17   472.6 2508.99
#Mann= 4 ,-1,0
       0      .1       0   144.6    .045       0  160.82      .1       0
  440.05     .06       0
#XS Ineff= 2 , 0
                          258.03         2504.72
Permanent Ineff=
       F       F
Bank Sta=144.6,160.82
XS Rating Curve= 0 ,0
Exp/Cntr(USF)=0,0
Exp/Cntr=0.3,0.1

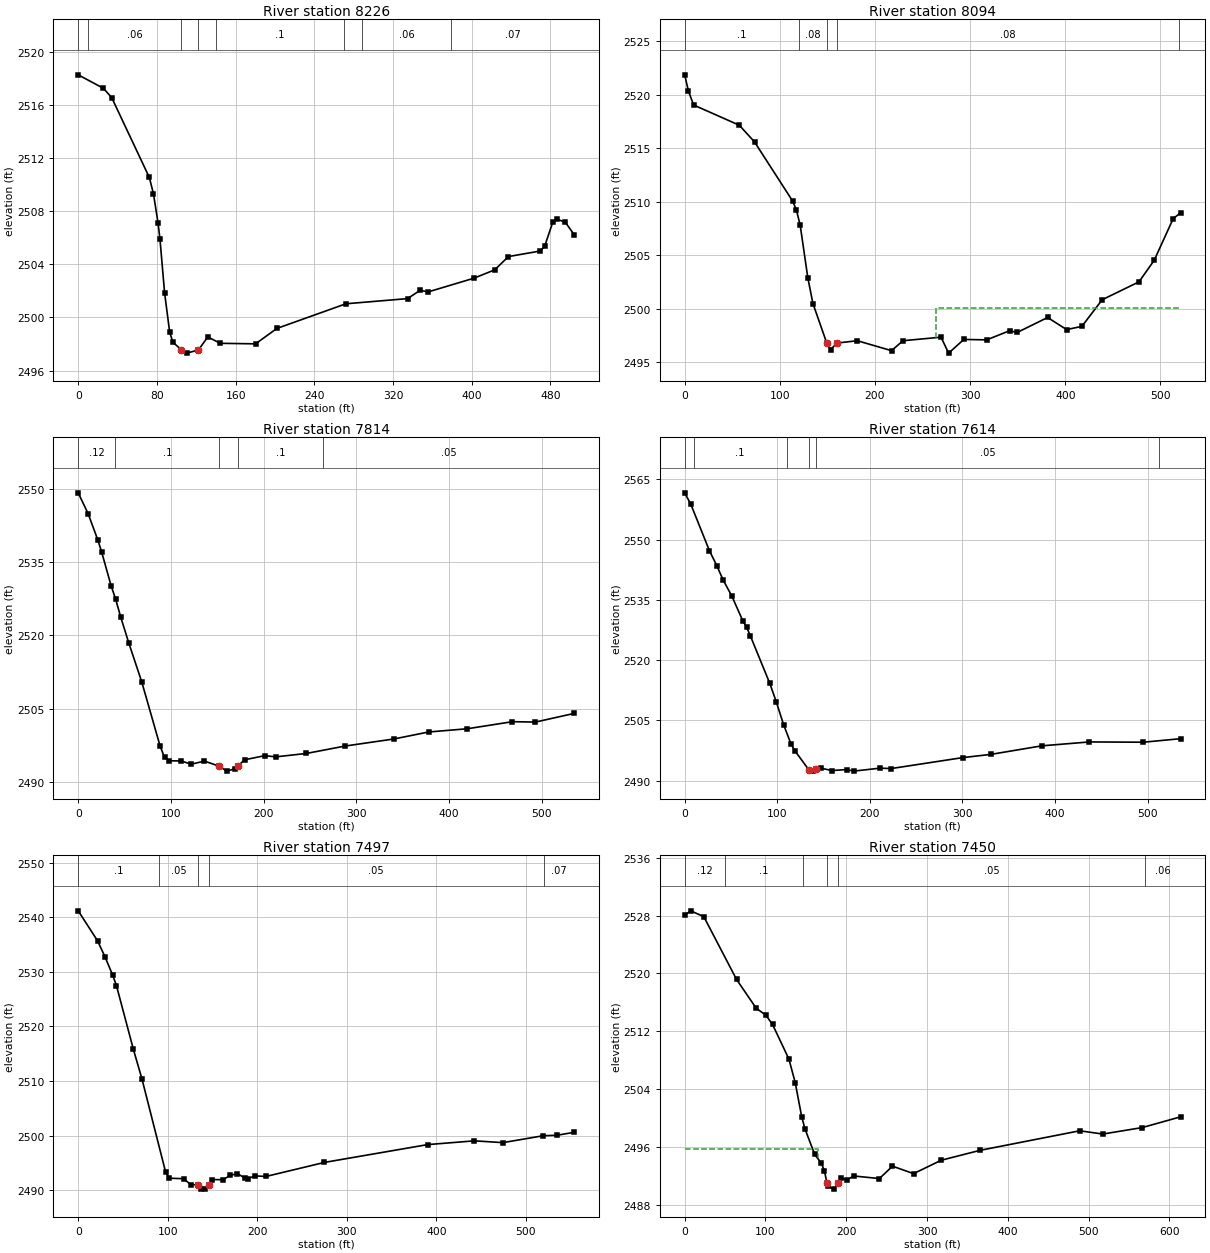
Type RM Length L Ch R = 1 ,8226    ,124.6,132.3,142.3
XS GIS Cut Line= 3
2293054.67140307504047.6646563352292860.78747236504261.353934806
2292791.98994856 504465.66173276
#Sta/Elev= 30
       0 2518.29    25.5 2517.28      34 2516.58    72.3 2510.55    76.5 2509.32
    81.1 2507.14    83.1 2505.91    87.8 2501.85      93 2498.87    96.3 2498.13
   104.8 2497.56   110.4 2497.31  122.24 2497.55   131.7 2498.53   144.4 2498.05
   180.3 2498.01   201.9 2499.17   272.1 2501.03   334.8 2501.42   347.4 2502.04
   355.9 2501.93   402.3 2502.96   423.4 2503.59   437.3 2504.59   469.8 2505.01
   474.1 2505.36   482.5 2507.21   486.7 2507.41   495.2 2507.17   504.1 2506.24
#Mann= 8 ,-1,0
       0      .1       0      10     .06       0   104.8    .045       0
  122.24     .06       0     140      .1       0     270     .05       0
  288.54     .06       0  378.54     .07       0
Bank Sta=104.8,122.24
XS Rating Curve= 0 ,0
Exp/Cntr(USF)=0,0
Exp/Cntr=0.3,0.1

Type RM Length L Ch R = 1 ,8094    ,264.6,279.6,283.5
XS GIS Cut Line= 2
2293081.55691771504030.6253858952292560.35550596504030.625385895
#Sta/Elev= 30
       0 2521.84     3.9 2520.33     9.4 2519.02    57.4 2517.13    73.4 2515.57
   113.4 2510.05   117.4 2509.21   121.4 2507.78   129.4 2502.88   134.8 2500.46
   149.4 2496.75   153.4 2496.16   159.9 2496.77   181.4 2496.99   217.4 2496.06
   229.4 2496.99   269.4 2497.32   277.4 2495.83   293.4 2497.11   317.4 2497.07
   341.4 2497.92   349.4 2497.76   381.4 2499.16   401.4 2498.03   417.4 2498.33
   438.8 2500.82   477.4 2502.49   493.4  2504.5   513.4  2508.4   521.2 2508.95
#Mann= 5 ,-1,0
       0      .1       0     120     .08       0   149.4    .045       0
   159.9     .08       0     520     .06       0
#XS Ineff= 2 , 0
                          264.34         2500.01
Permanent Ineff=
       F       F
Bank Sta=149.4,159.9
XS Rating Curve= 0 ,0
Exp/Cntr(USF)=0,0
Exp/Cntr=0.3,0.1

Type RM Length L Ch R = 1 ,7814    ,203.6,199.5,194
XS GIS Cut Line= 3
2293085.76905872503898.4954286252292882.18948378503763.718210036
2292599.49662404503831.700593091
#Sta/Elev= 30
       0 2549.17    10.8 2544.85    21.1 2539.54    25.2 2537.11    35.5 2530.14
    40.3 2527.44    45.9 2523.71    54.7 2518.35    68.5 2510.49    88.3 2497.35
    93.1 2495.01    97.9 2494.33   111.1 2494.29   121.8 2493.63   136.2 2494.26
   152.2 2493.21   160.2 2492.21     169 2492.69   172.4 2493.29   179.4 2494.53
   201.3 2495.38     213 2495.13   246.2 2495.83   287.4 2497.33   340.8  2498.8
   377.9 2500.22   419.5 2500.88   468.4 2502.33   493.1 2502.25   534.9 2504.02
#Mann= 5 ,-1,0
       0     .12       0      40      .1       0   152.2    .045       0
   172.4      .1       0  264.15     .05       0
Bank Sta=152.2,172.4
XS Rating Curve= 0 ,0
Exp/Cntr(USF)=0,0
Exp/Cntr=0.3,0.1

Type RM Length L Ch R = 1 ,7614    ,117.4,117.4,116.3
XS GIS Cut Line= 3
2293166.90290329503644.4587726422292895.28096445 503631.64227461
2292641.70336867503703.911783935
#Sta/Elev= 30
       0 2561.66     6.7 2558.77    26.8 2547.21    34.8 2543.47    41.4 2540.01
    50.8 2536.01    62.8 2529.77    66.8 2528.26    70.9 2526.05    91.9 2514.21
    98.8 2509.69   106.8 2503.94   114.9 2499.07   118.9 2497.45   133.9 2492.74
   134.9 2492.41   138.1 2492.35   142.3 2492.85   146.9  2493.1   158.9  2492.5
   174.9 2492.73   182.9 2492.36     211 2493.09     223 2492.99   300.1 2495.71
   330.7 2496.52   385.7 2498.65   437.1 2499.62   495.3 2499.55   535.6 2500.43
#Mann= 6 ,-1,0
       0     .12       0      10      .1       0     110     .05       0
   133.9    .045       0   142.3     .05       0  511.92     .07       0
Bank Sta=133.9,142.3
XS Rating Curve= 0 ,0
Exp/Cntr=0.3,0.1

Type RM Length L Ch R = 1 ,7497    ,47.5,47.7,47.7
BEGIN DESCRIPTION:
structure xs 4
END DESCRIPTION:
XS GIS Cut Line= 4
2293140.56784341503555.1438857152293051.27334395  503524.3508136
2292926.27580704503530.8389215962292629.38237534503684.330491676
#Sta/Elev= 30
       0 2541.16    21.6 2535.67      30 2532.71    38.5 2529.38    42.7 2527.47
    61.6 2515.81    71.1 2510.44    97.6 2493.34   101.6 2492.22   117.6 2492.13
   125.6 2491.06  133.612490.978   137.6 2490.22   141.6 2490.23  146.062490.961
   149.6 2491.97   161.6 2491.94   169.7 2492.72   177.7 2493.08   185.7 2492.28
   189.6 2492.16   197.7 2492.64   209.7 2492.54     275 2495.11   390.2 2498.37
   442.5 2499.06   474.2 2498.73   519.2 2499.99   534.6 2500.08   553.8 2500.62
#Mann= 5 ,-1,0
       0      .1       0      90     .05       0  133.61    .045       0
  146.06     .05       0  519.62     .07       0
Bank Sta=133.61,146.06
XS Rating Curve= 0 ,0
Exp/Cntr(USF)=0,0
Exp/Cntr=0.5,0.3

Type RM Length L Ch R = 1 ,7450    ,46.8,46.6,46.9
BEGIN DESCRIPTION:
structure xs 3
END DESCRIPTION:
XS GIS Cut Line= 4
2293199.56885109 503500.50326084 2293074.3116826503480.993551576
2292941.85619481503485.4458368792292620.98471787503636.234817098
#Sta/Elev= 30
       0 2528.07     7.5 2528.65    23.7 2527.84    64.2 2519.17    88.4 2515.21
   100.6 2514.21   108.7 2512.96     129 2508.17   136.8 2504.92   144.9 2500.16
   148.9 2498.52   160.9    2495   168.9 2493.82   172.9 2492.77   176.12491.018
   176.9 2490.58   184.9  2490.2   189.9 2491.01   192.9 2491.74   200.9 2491.46
     209 2492.02     241 2491.66   257.2 2493.37   283.3 2492.34   317.5 2494.19
   365.6 2495.56   488.9 2498.26   517.5 2497.81   566.1  2498.7   613.8 2500.19
#Mann= 6 ,-1,0
       0     .12       0      50      .1       0  146.77     .05       0
   176.1    .045       0   189.9     .05       0   569.3     .06       0
#XS Ineff= 2 , 0
           164.6 2495.76   201.4         2491.31
Permanent Ineff=
       F       F
Bank Sta=176.1,189.9
XS Rating Curve= 0 ,0
Exp/Cntr(USF)=0,0
Exp/Cntr=0.5,0.3

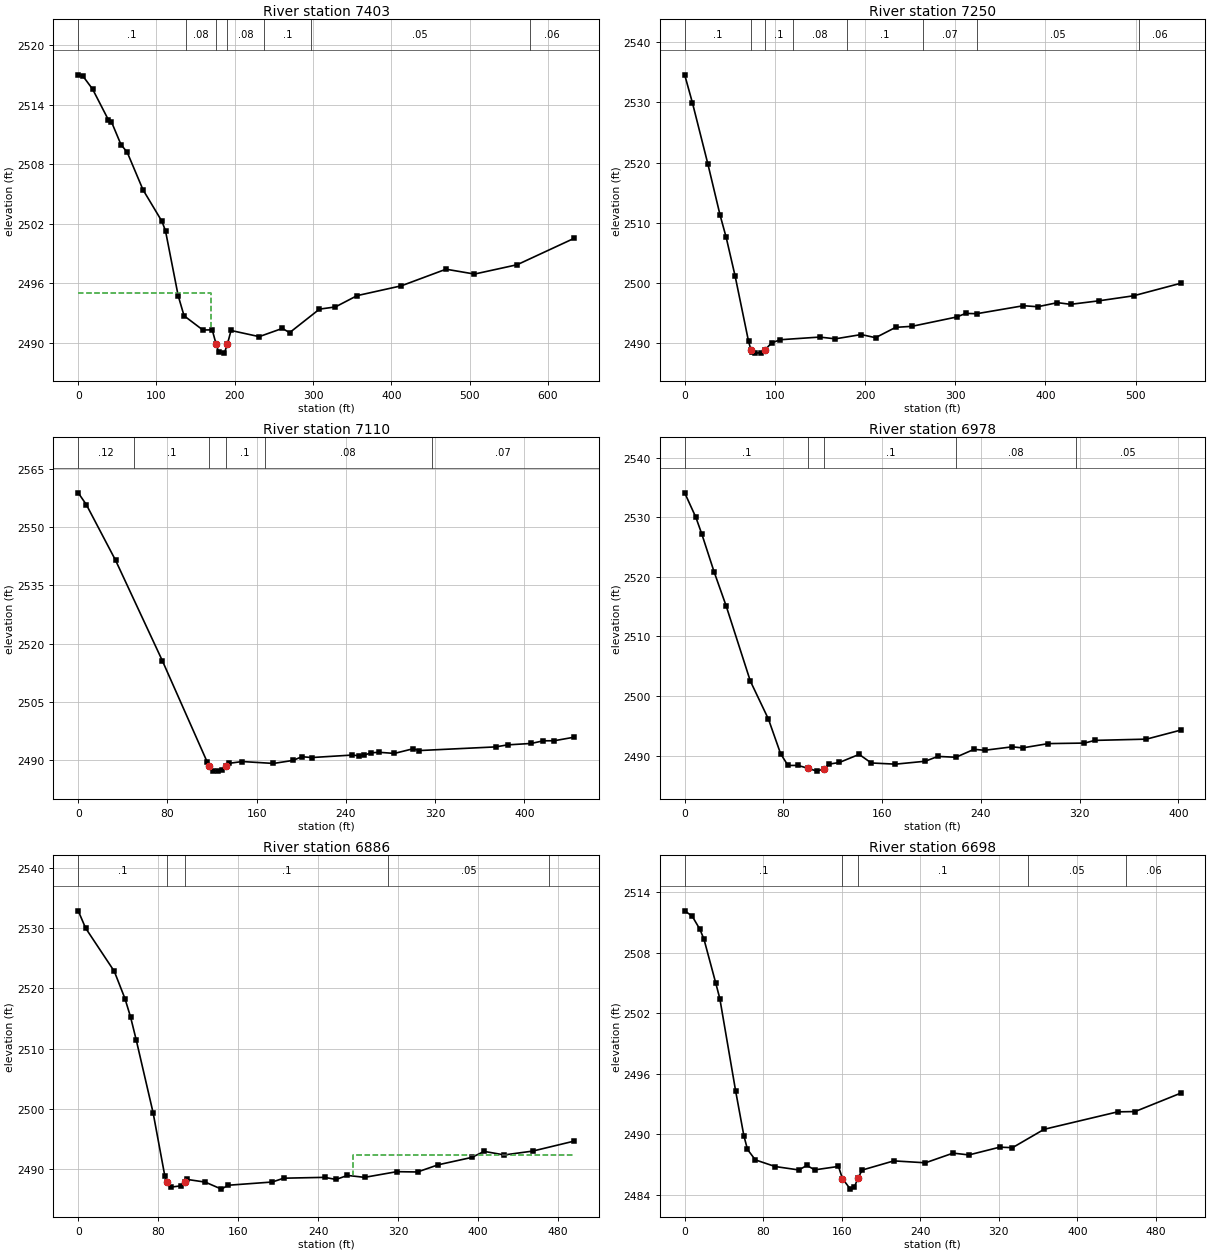
Type RM Length L Ch R = 1 ,7403    ,160.7,153.2,140.4
BEGIN DESCRIPTION:
structure xs 2
END DESCRIPTION:
XS GIS Cut Line= 4
2293194.31569577503450.7229294412293067.58741038503434.691037915
2292948.49335904503438.5081549452292608.00651997503621.729772385
#Sta/Elev= 30
       0    2517     6.2 2516.85    18.3 2515.57    38.4 2512.49    42.5 2512.26
    54.6 2509.98    62.6  2509.2    82.8 2505.42     107 2502.24   111.5 2501.29
   127.7 2494.76   135.2 2492.74   159.2 2491.31   171.2 2491.32   176.1  2489.9
   179.2 2489.13   186.6 2488.98  190.482489.853   195.2 2491.26   231.2 2490.64
   260.8 2491.47     270 2491.04   308.2 2493.41   328.5 2493.63   356.3 2494.77
   412.9 2495.76   469.8 2497.43   506.2 2496.94   560.7 2497.88   633.5 2500.54
#Mann= 7 ,-1,0
       0      .1       0  137.74     .08       0   176.1    .045       0
  190.48     .08       0  237.74      .1       0  296.89     .05       0
  576.89     .06       0
#XS Ineff= 2 , 0
           170.2    2495   196.6            2490
Permanent Ineff=
       F       F
Bank Sta=176.1,190.48
XS Rating Curve= 0 ,0
Exp/Cntr(USF)=0,0
Exp/Cntr=0.5,0.3

Type RM Length L Ch R = 1 ,7250    ,137.4,140.1,143.4
XS GIS Cut Line= 3
2293040.10416776503236.9643757632292863.76702098503419.529547057
2292619.50943901503586.640912614
#Sta/Elev= 30
       0 2534.59     8.6 2529.93    25.6 2519.82    39.2 2511.27      46 2507.54
    55.9 2501.12    70.8 2490.24    73.42488.859    74.7 2488.45    78.2 2488.28
      85 2488.34    89.3 2488.86    96.3 2489.98     106 2490.51   149.6 2490.95
   167.1 2490.66   195.7 2491.37   211.6 2490.85   233.9 2492.57   251.9 2492.74
   301.8  2494.3   311.5 2494.89   323.8 2494.84   375.6 2496.17   391.3    2496
   413.3 2496.68   427.8  2496.4     459 2496.98   497.6 2497.82   549.8  2499.9
#Mann= 8 ,-1,0
       0      .1       0    73.4    .045       0    89.3      .1       0
     120     .08       0     180      .1       0  263.82     .07       0
  323.82     .05       0  503.82     .06       0
Bank Sta=73.4,89.3
XS Rating Curve= 0 ,0
Exp/Cntr=0.3,0.1

Type RM Length L Ch R = 1 ,7110    ,133.4,132,131.4
XS GIS Cut Line= 3
2292998.43076843503125.3557222712292873.53774692503203.108066968
2292676.21799712503425.925844188
#Sta/Elev= 30
       0 2558.81     7.3 2555.76    33.5 2541.43    75.4  2515.6   115.7 2489.46
   117.7  2488.4   120.6  2487.3   125.2 2487.14   129.3 2487.48   132.2 2488.38
   135.1 2489.14   147.1 2489.61   175.1 2489.12   192.6  2489.9   200.6 2490.85
   209.5 2490.64   245.7 2491.28   251.6  2491.1   256.7 2491.24   262.1 2491.85
   269.8 2491.99   283.5  2491.7     300 2492.88     306 2492.44   374.3 2493.38
     385  2493.9   406.3 2494.27     417 2494.95   426.7 2494.96   444.7 2495.88
#Mann= 6 ,-1,0
       0     .12       0      50      .1       0   117.7    .045       0
   132.2      .1       0  167.12     .08       0  317.12     .07       0
Bank Sta=117.7,132.2
XS Rating Curve= 0 ,0
Exp/Cntr(USF)=0,0
Exp/Cntr=0.3,0.1

Type RM Length L Ch R = 1 ,6978    ,95.9,91.9,91
XS GIS Cut Line= 3
2292887.62856297503036.8409913652292686.18696096503179.282960982
2292640.67295884503327.624893837
#Sta/Elev= 30
       0  2534.1     9.1 2529.97      14 2527.11    23.8 2520.86    33.6 2515.12
    53.2  2502.5    67.9  2496.1    77.7 2490.32    83.7 2488.33    91.7 2488.34
   99.79 2487.87   107.1 2487.38  113.25 2487.79   116.9 2488.55   125.3 2488.83
   141.4 2490.19   151.2 2488.75   170.8 2488.55     195 2489.04   205.1 2489.85
   219.8 2489.71   234.5 2491.04   243.1 2490.88   265.4 2491.46   273.8 2491.28
   294.7    2492     324 2492.09   332.4 2492.54   374.2 2492.75   401.9 2494.26
#Mann= 5 ,-1,0
       0      .1       0   99.79    .045       0  113.25      .1       0
     220     .08       0  316.72     .05       0
Bank Sta=99.79,113.25
XS Rating Curve= 0 ,0
Exp/Cntr(USF)=0,0
Exp/Cntr=0.3,0.1

Type RM Length L Ch R = 1 ,6886    ,198.8,187.7,180.4
XS GIS Cut Line= 3
2292841.55775352 502943.926549812292601.49539774503186.599815341
2292561.46389621503336.045688937
#Sta/Elev= 30
       0 2532.83     7.4 2529.97    36.1 2522.81    46.8 2518.28    52.4 2515.23
      58 2511.47    74.9 2499.41    86.7 2488.87    88.6 2487.99      93 2487.09
     103  2487.3   106.5    2488   109.3 2488.35   127.1 2487.91   143.3 2486.75
   149.8 2487.39   194.2 2487.93   205.5 2488.56   246.5  2488.7   257.9 2488.35
   269.3 2489.02   286.4  2488.7   318.7 2489.64   339.4 2489.59   360.1 2490.78
   393.7    2492   406.1    2493   426.2 2492.41   454.7 2493.05   496.1  2494.7
#Mann= 5 ,-1,0
       0      .1       0    88.6    .045       0   106.5      .1       0
     310     .05       0  471.35     .06       0
#XS Ineff= 2 , 0
                          274.65         2492.44
Permanent Ineff=
       F       F
Bank Sta=88.6,106.5
XS Rating Curve= 0 ,0
Exp/Cntr=0.3,0.1

Type RM Length L Ch R = 1 ,6698    ,290.1,282.4,274
XS GIS Cut Line= 2
  2292611.823637502821.6620429012292550.74976452 503323.23122064
#Sta/Elev= 30
       0 2512.15     7.6 2511.63    15.6  2510.3    19.7 2509.32    31.7 2504.97
    35.8 2503.45    51.9  2494.3    60.3 2489.86      64 2488.49      72 2487.46
    92.2  2486.8   116.4 2486.46   124.4 2486.91   132.5 2486.47   156.7 2486.81
   160.7 2485.61   168.8 2484.56   172.8 2484.74   176.42485.616   180.8 2486.45
   213.1 2487.36   245.3 2487.17   273.5 2488.13   289.6 2487.95     321 2488.72
     334 2488.67   366.2 2490.49   441.1 2492.22   458.9 2492.25   505.3 2494.07
#Mann= 5 ,-1,0
       0      .1       0   160.7    .045       0   176.4      .1       0
     350     .05       0     450     .06       0
Bank Sta=160.7,176.4
XS Rating Curve= 0 ,0
Exp/Cntr(USF)=0,0
Exp/Cntr=0.3,0.1

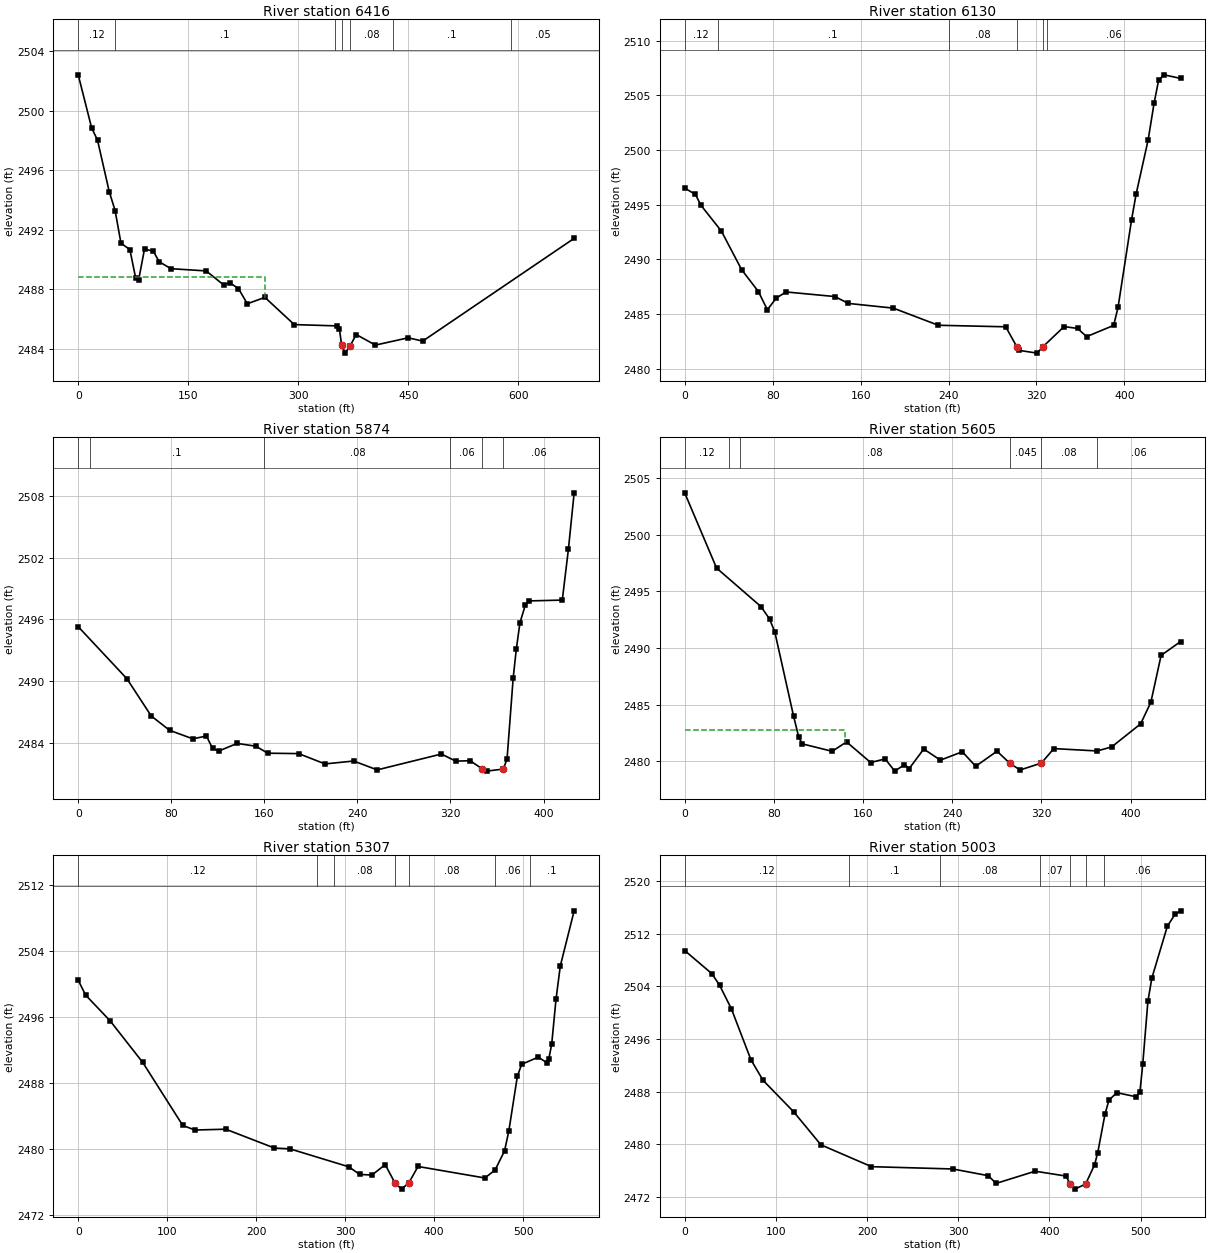
Type RM Length L Ch R = 1 ,6416    ,272.1,286,292.5
XS GIS Cut Line= 3
2292291.47582825502626.8808267262292303.84328743502936.067306155
2292520.96090409503231.512164277
#Sta/Elev= 30
       0 2502.41    18.3 2498.84    26.3 2498.02    42.3 2494.55    50.3 2493.28
    58.3 2491.08    70.4 2490.66    78.4 2488.72    82.4 2488.62    90.4  2490.7
   102.4 2490.54   110.4 2489.84   126.4 2489.37   174.4 2489.22   198.5 2488.27
   206.5 2488.43   218.5 2488.03   230.5 2487.01   254.5 2487.44   294.5 2485.61
   353.4 2485.52   356.2 2485.28   359.1 2484.22     364 2483.69   370.8  2484.2
   379.1 2484.94   405.1 2484.23   449.8 2484.72   469.7  2484.5   676.1 2491.41
#Mann= 7 ,-1,0
       0     .12       0      50      .1       0  349.43     .08       0
   359.1    .045       0   370.8     .08       0  429.43      .1       0
  589.43     .05       0
#XS Ineff= 2 , 0
          253.97 2488.83
Permanent Ineff=
       F       F
Bank Sta=359.1,370.8
XS Rating Curve= 0 ,0
Exp/Cntr(USF)=0,0
Exp/Cntr=0.3,0.1

Type RM Length L Ch R = 1 ,6130    ,245.5,255.5,261.3
XS GIS Cut Line= 2
2292224.06156997502647.5956003272292130.01510674 503088.80893257
#Sta/Elev= 30
       0 2496.52     9.8 2495.94    14.7 2494.96    33.4 2492.58    51.8 2489.05
    67.1 2487.04    75.2 2485.38    83.4 2486.46    92.3 2487.01   136.6 2486.59
   148.9 2485.96   189.8 2485.53   230.7 2483.96     292 2483.82   302.22481.982
   304.3 2481.66   320.6 2481.41   325.6 2481.97   345.1 2483.84   357.4 2483.67
   365.6 2482.92   390.2 2483.95   394.2 2485.61   406.5 2493.63   410.6 2495.96
   421.6 2500.95     427 2504.32   431.1  2506.4   436.1 2506.89   451.1 2506.56
#Mann= 6 ,-1,0
       0     .12       0      30      .1       0     240     .08       0
   302.2    .045       0   325.6     .08       0     330     .06       0
Bank Sta=302.2,325.6
XS Rating Curve= 0 ,0
Exp/Cntr=0.3,0.1

Type RM Length L Ch R = 1 ,5874    ,260.3,269.4,276.2
XS GIS Cut Line= 2
2292179.64033944502641.5730061712291901.82084808502964.947468588
#Sta/Elev= 30
       0 2495.29    41.9 2490.23    62.8 2486.62    78.6 2485.23    98.6  2484.4
   110.2 2484.68   115.5 2483.47   120.8 2483.22   136.6 2483.96   152.6 2483.69
     163 2483.01   189.5 2482.97   212.1 2481.97   236.8 2482.25     257 2481.39
   312.2 2482.93   324.5 2482.24   336.9 2482.28   347.5 2481.47   351.1 2481.27
   365.3 2481.47   368.6 2482.42   373.9 2490.32   376.6 2493.13   379.7 2495.67
   384.4 2497.41   387.9 2497.79   416.1 2497.87   421.4 2502.84   426.3 2508.28
#Mann= 6 ,-1,0
       0     .12       0      10      .1       0     160     .08       0
     320     .06       0   347.5    .045       0   365.3     .06       0
Bank Sta=347.5,365.3
XS Rating Curve= 0 ,0
Exp/Cntr(USF)=0,0
Exp/Cntr=0.3,0.1

Type RM Length L Ch R = 1 ,5605    ,300.9,297.7,295.1
XS GIS Cut Line= 2
2292118.55477181502558.2200545322291706.99729779502726.822480274
#Sta/Elev= 30
       0 2503.71    28.6 2497.07    68.5 2493.66    76.1 2492.57    80.8 2491.44
    97.7 2483.98   102.2 2482.18   105.3 2481.55   132.3 2480.89   145.2 2481.72
   166.8  2479.9   179.8 2480.22   188.4 2479.14   197.1 2479.71   201.4 2479.37
   214.4 2481.09   229.4 2480.11     249 2480.85     261 2479.57   280.1  2480.9
   291.8 2479.82   300.8 2479.24   319.9 2479.85   331.1 2481.13     370 2480.92
     383 2481.28   408.9 2483.31   418.1 2485.22   427.3 2489.36   444.8 2490.58
#Mann= 6 ,-1,0
       0     .12       0      40      .1       0      50     .08       0
   291.8    .045       0   319.9     .08       0     370     .06       0
#XS Ineff= 2 , 0
          143.94 2482.73
Permanent Ineff=
       F       F
Bank Sta=291.8,319.9
XS Rating Curve= 0 ,0
Exp/Cntr(USF)=0,0
Exp/Cntr=0.3,0.1

Type RM Length L Ch R = 1 ,5307    ,297.4,304.2,305.4
XS GIS Cut Line= 3
2291964.57033633 502186.006540252291916.44130492502271.281764761
2291535.27506617502527.634091263
#Sta/Elev= 30
       0 2500.47     8.2 2498.68    35.8 2495.56    72.5 2490.52   117.5 2482.89
   131.2 2482.34   165.8 2482.44   220.5 2480.16     238 2480.06   304.1 2477.89
   316.3 2476.97     330 2476.89     345 2478.15     356 2475.92   363.4 2475.19
   371.6 2475.97   381.9 2477.93   456.9 2476.54   468.4 2477.49   479.1 2479.82
   483.9 2482.23   493.5 2488.85   498.3 2490.29     517 2491.16   527.3 2490.43
   528.9 2490.97   532.1 2492.76   536.9 2498.15   541.7 2502.17   557.3 2508.86
#Mann= 7 ,-1,0
       0     .12       0  267.92      .1       0  287.92     .08       0
     356    .045       0   371.6     .08       0  467.92     .06       0
  507.92      .1       0
Bank Sta=356,371.6
XS Rating Curve= 0 ,0
Exp/Cntr=0.3,0.1

Type RM Length L Ch R = 1 ,5003    ,273.3,285.8,292.5
XS GIS Cut Line= 2
2291944.13931665502118.5859212842291434.53211807502309.024508024
#Sta/Elev= 30
       0 2509.44    29.9 2505.92    38.4 2504.14    51.2  2500.6    72.6 2492.88
    85.9 2489.74   119.5 2484.96   149.4 2479.94   204.9 2476.62   294.2 2476.27
     333 2475.25   341.6 2474.08   384.5 2475.93   418.4 2475.19   422.7 2474.01
   427.9 2473.21   439.8 2473.98   449.6  2476.9   453.1 2478.76   461.1 2484.63
   465.4 2486.72     474 2487.86   495.3 2487.23   499.4 2488.03   502.5 2492.24
   508.1 2501.72   512.4 2505.23   529.5 2513.15     538 2514.97     544 2515.47
#Mann= 7 ,-1,0
       0     .12       0     180      .1       0     280     .08       0
     390     .07       0   422.7    .045       0   439.8     .07       0
     460     .06       0
Bank Sta=422.7,439.8
XS Rating Curve= 0 ,0
Exp/Cntr=0.3,0.1