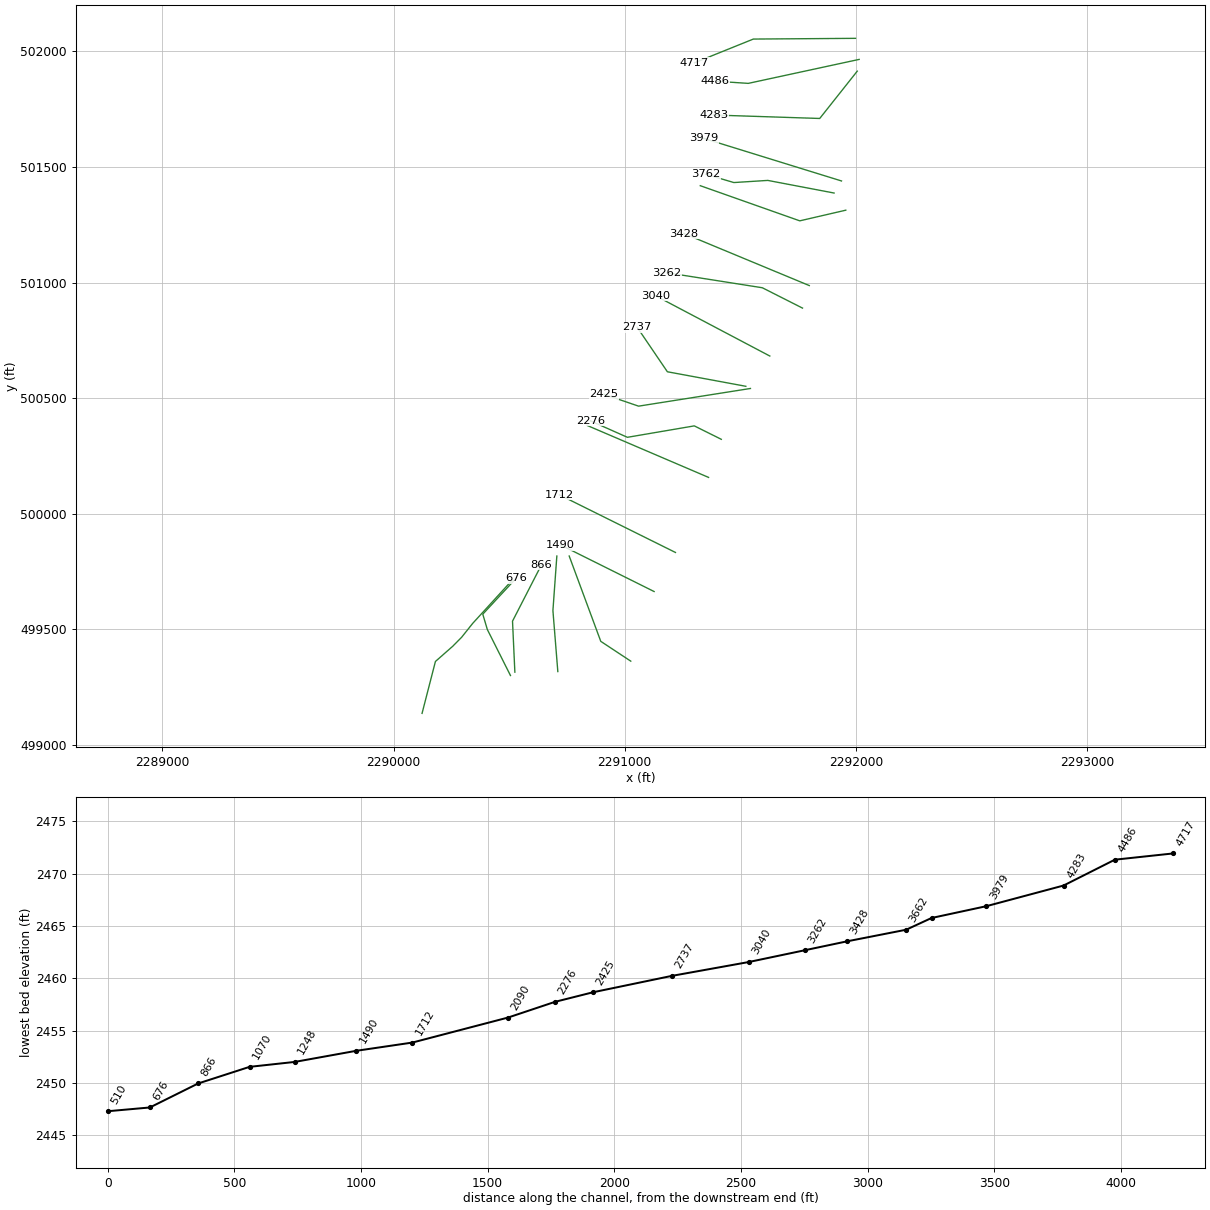
HEC-RAS study MOORERN1.prj: MOORERN1

--- MOORERN1.g01 (geometry) --- (continued)

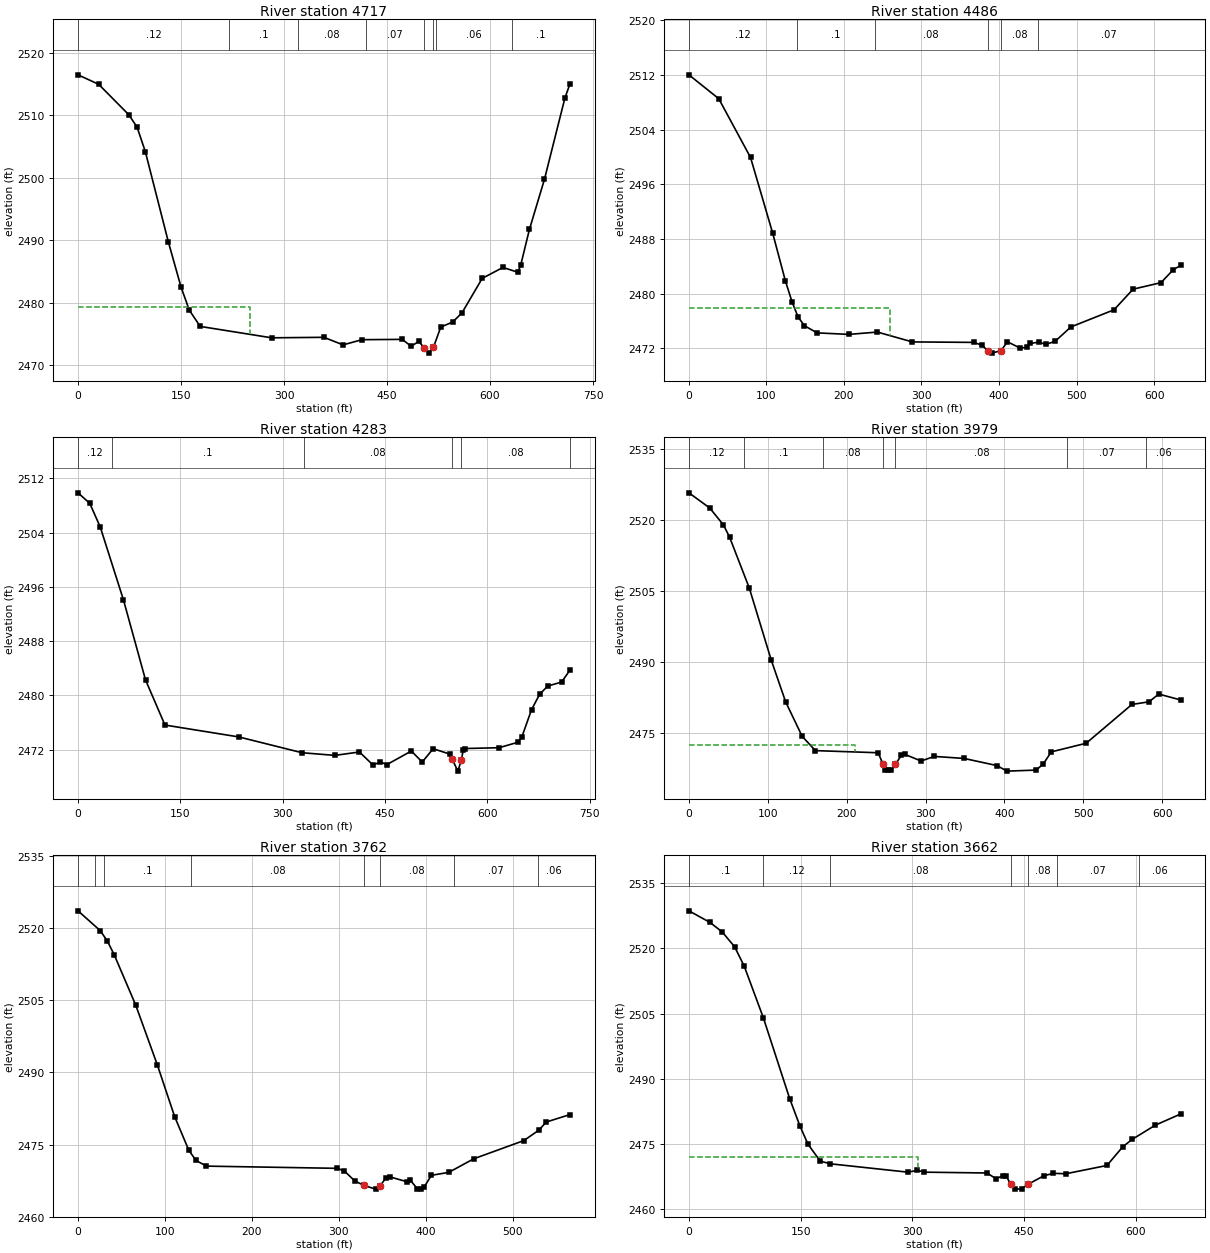
Type RM Length L Ch R = 1 ,4717    ,232.8,231.3,226.8
XS GIS Cut Line= 3
 2291998.1244677 502056.601657452291556.19761265502053.459997343
2291301.72314399501950.832433848
#Sta/Elev= 30
       0 2516.44      30 2514.93      74 2510.05      86 2508.07      98 2504.16
   131.5 2489.73     150  2482.5     162  2478.8     178 2476.19     282 2474.37
     358 2474.45     386 2473.24   413.5 2474.07   472.2 2474.12   485.1 2473.01
   496.2  2473.8   503.6 2472.82     511 2471.92   517.6 2472.85   528.2 2476.09
   545.5 2476.89     559 2478.34   588.6 2483.88   618.8 2485.63   640.4 2484.86
   644.7 2486.03   657.3  2491.7   679.2 2499.72   708.9 2512.69   716.3 2514.97
#Mann= 8 ,-1,0
       0     .12       0     220      .1       0     320     .08       0
     420     .07       0   503.6    .045       0   517.6     .07       0
  521.94     .06       0  631.94      .1       0
#XS Ineff= 2 , 0
          250.14  2479.3
Permanent Ineff=
       F       F
Bank Sta=503.6,517.6
XS Rating Curve= 0 ,0
Exp/Cntr(USF)=0,0
Exp/Cntr=0.3,0.1

Type RM Length L Ch R = 1 ,4486    ,203.7,202.6,195.8
XS GIS Cut Line= 3
2292013.83276824501965.4935143472291534.20599191501861.818730817
2291390.73684702501871.243711138
#Sta/Elev= 30
       0 2512.02    38.5 2508.53    79.5 2499.93   108.1 2488.85   124.5 2481.86
   132.9 2478.86   140.8 2476.61     149 2475.33   165.4 2474.28   206.3 2474.06
   243.1  2474.4   288.2 2472.96   367.2 2472.89   378.2 2472.48   385.3 2471.68
   390.5 2471.32   402.7 2471.69   410.9 2472.98   427.3 2472.05   435.5 2472.18
   440.3 2472.73   451.9 2472.94     460 2472.59   472.3 2473.04   492.7 2475.15
   548.4 2477.66   572.9 2480.67     609 2481.63     625 2483.55   634.5 2484.15
#Mann= 6 ,-1,0
       0     .12       0     140      .1       0     240     .08       0
   385.3    .045       0   402.7     .08       0     450     .07       0
#XS Ineff= 2 , 0
          259.89 2477.85
Permanent Ineff=
       F       F
Bank Sta=385.3,402.7
XS Rating Curve= 0 ,0
Exp/Cntr(USF)=0,0
Exp/Cntr=0.3,0.1

Type RM Length L Ch R = 1 ,4283    ,304.8,304.4,295.9
XS GIS Cut Line= 3
2292005.58573111501914.6907040472291843.31180737501710.046269625
2291383.95949521 501725.01706251
#Sta/Elev= 30
       0 2509.86    17.2 2508.31    32.6 2504.82    66.6 2494.08    98.9  2482.3
   127.4 2475.64   235.6 2473.89   328.3 2471.56   376.4 2471.17   412.4 2471.67
   432.4 2469.74   443.2 2470.22   452.4  2469.8   488.4 2471.81   504.4 2470.19
   520.4 2472.15   544.5 2471.37   548.5 2470.59   556.5 2468.85   561.8 2470.49
   564.5 2472.02   567.3 2472.18     617  2472.3   644.5  2473.1   650.1 2473.81
   664.5 2477.89   676.5 2480.19   688.5  2481.4   708.5 2481.97   720.8 2483.72
#Mann= 6 ,-1,0
       0     .12       0      50      .1       0  331.17     .08       0
   548.5    .045       0   561.8     .08       0  720.77     .07       0
Bank Sta=548.5,561.8
XS Rating Curve= 0 ,0
Exp/Cntr=0.3,0.1

Type RM Length L Ch R = 1 ,3979    ,199.8,216.7,216.1
XS GIS Cut Line= 2
2291937.38570564501439.7890564452291341.51750534501624.099782721
#Sta/Elev= 30
       0 2525.78    26.4 2522.57    43.7 2519.01    51.5 2516.43    76.6 2505.61
   104.4 2490.37   122.7 2481.52   143.6 2474.24   160.4 2471.22   239.9 2470.77
     2462468.403   248.3 2467.22   252.5 2467.09   256.7 2467.12   261.9 2468.31
   269.2 2470.21   273.4 2470.45   294.4 2469.02   311.1 2469.99   348.8 2469.57
   390.7 2468.05   403.2 2466.88   440.2  2467.1   449.3 2468.39   459.4 2470.95
   503.7 2472.78   561.7 2480.99   583.3 2481.55   595.8 2483.19   623.7 2481.93
#Mann= 7 ,-1,0
       0     .12       0      70      .1       0     170     .08       0
     246    .045       0   261.9     .08       0     480     .07       0
     580     .06       0
#XS Ineff= 2 , 0
          210.99 2472.49
Permanent Ineff=
       F       F
Bank Sta=246,261.9
XS Rating Curve= 0 ,0
Exp/Cntr(USF)=0,0
Exp/Cntr=0.3,0.1

Type RM Length L Ch R = 1 ,3762    ,107,100.1,96
XS GIS Cut Line= 4
2291905.38027708501387.5669746332291618.42162949501442.170441988
2291472.03786595501432.8762347792291350.05139632501468.891287715
#Sta/Elev= 30
       0 2523.58    25.7 2519.44    33.8 2517.28    41.9 2514.35    66.4 2503.99
    91.4  2491.5   111.2 2480.81   127.5 2473.82   135.8  2471.7   147.8 2470.53
   298.4 2470.07   306.5 2469.52   318.4 2467.45   329.1 2466.52   342.5 2465.75
   347.9 2466.48   354.5 2468.15   358.5 2468.32   378.1  2467.3   382.5 2467.56
   390.6  2465.8   394.6 2465.88   398.6 2466.27   406.6 2468.62   426.6 2469.23
   455.3 2472.05     513 2475.84   530.4 2478.02   538.7 2479.69     566 2481.24
#Mann= 8 ,-1,0
       0      .1       0      20     .12       0      30      .1       0
     130     .08       0   329.1    .045       0   347.9     .08       0
  432.11     .07       0  528.79     .06       0
Bank Sta=329.1,347.9
XS Rating Curve= 0 ,0
Exp/Cntr(USF)=0,0
Exp/Cntr=0.3,0.1

Type RM Length L Ch R = 1 ,3662    ,233.9,233.5,232.3
XS GIS Cut Line= 3
2291955.94940071501313.3487870972291756.93034703501267.306356006
2291326.68454738501419.307517004
#Sta/Elev= 30
       0 2528.61    28.5 2525.93    44.9 2523.72    61.4 2520.34    74.3 2515.88
     100 2504.01   135.3 2485.45     149 2479.19   159.9 2474.96   176.3 2471.08
     190 2470.45   294.1 2468.53   306.9 2468.95   316.1 2468.53   400.2 2468.34
   412.9 2466.98   421.4 2467.76   425.7 2467.71     432 2465.84   438.4 2464.63
   446.9 2464.69   455.4 2465.74   476.6  2467.7   489.3 2468.26   506.3 2468.17
   561.4 2470.07   582.6 2474.36   595.4 2476.08   626.4 2479.34   660.6 2481.92
#Mann= 7 ,-1,0
       0      .1       0     100     .12       0     190     .08       0
     432    .045       0   455.4     .08       0  494.28     .07       0
  604.28     .06       0
#XS Ineff= 2 , 0
          307.37 2471.92
Permanent Ineff=
       F       F
Bank Sta=432,455.4
XS Rating Curve= 0 ,0
Exp/Cntr=0.3,0.1

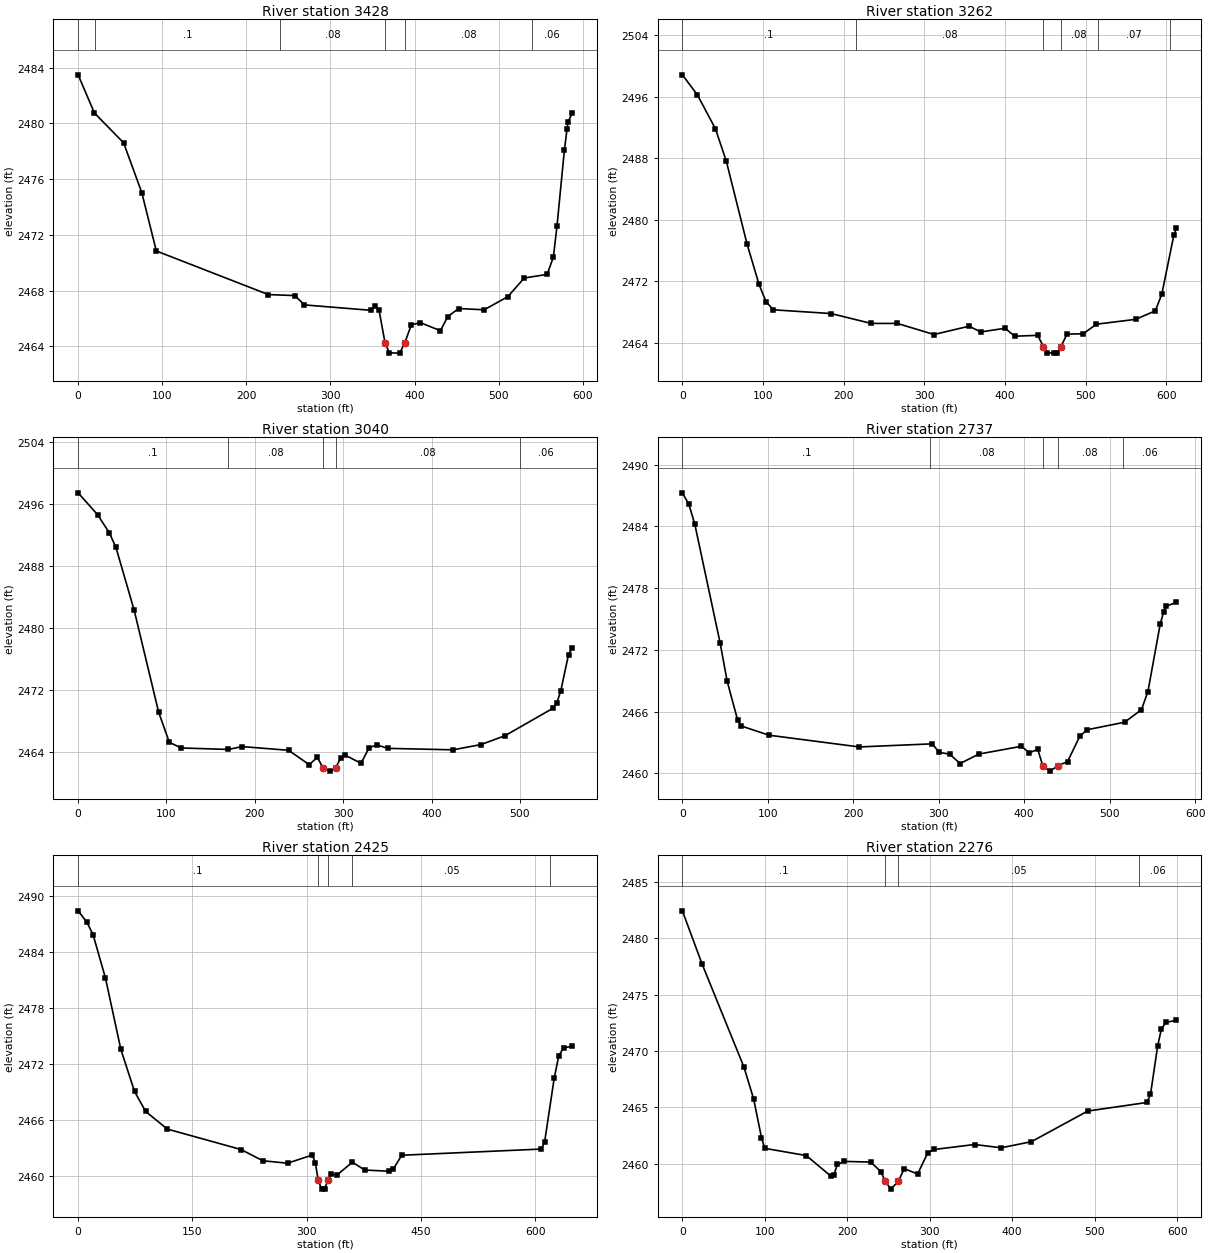
Type RM Length L Ch R = 1 ,3428    ,165.4,166.6,172.3
XS GIS Cut Line= 2
2291798.10544089500987.3900010392291255.64546242501212.542308706
#Sta/Elev= 30
       0 2483.49    19.4 2480.75    54.1 2478.61    75.7 2475.04      93 2470.85
   226.3 2467.72   257.6 2467.65   269.1 2466.98   348.6 2466.59   352.9 2466.88
   357.9 2466.58   364.92464.267   370.1 2463.54   382.4 2463.52   388.5 2464.27
   396.2 2465.55   406.8 2465.71   430.8 2465.13   439.5 2466.14   452.5 2466.72
   482.8 2466.63   510.9 2467.57   530.5 2468.91   557.7 2469.17   565.1 2470.41
   569.4 2472.64   578.2 2478.09   581.3 2479.57   582.4 2480.08   587.3 2480.73
#Mann= 6 ,-1,0
       0     .12       0      20      .1       0     240     .08       0
   364.9    .045       0   388.5     .08       0     540     .06       0
Bank Sta=364.9,388.5
XS Rating Curve= 0 ,0
Exp/Cntr(USF)=0,0
Exp/Cntr=0.3,0.1

Type RM Length L Ch R = 1 ,3262    ,223.6,222.2,218
XS GIS Cut Line= 3
2291768.78327989500889.9985377222291594.94475397500977.965020718
2291182.34005992501042.892662929
#Sta/Elev= 30
       0 2498.83    18.6 2496.23      41 2491.82    54.5 2487.61    80.2 2476.85
    95.1 2471.59   103.8 2469.34   112.8  2468.3   184.5 2467.81   234.1 2466.53
   266.5 2466.53     312 2465.09   355.6 2466.17   369.9 2465.42   400.1  2465.9
   412.2 2464.87   440.6 2464.98   447.82463.505   452.7 2462.72   460.8 2462.67
   464.9 2462.67   469.5 2463.53     477 2465.14     497 2465.18   513.5 2466.43
   562.1 2467.06   586.4 2468.16   594.5 2470.31   609.4 2477.97   612.5 2478.87
#Mann= 6 ,-1,0
       0      .1       0  214.83     .08       0   447.8    .045       0
   469.5     .08       0  514.83     .07       0  604.83     .06       0
Bank Sta=447.8,469.5
XS Rating Curve= 0 ,0
Exp/Cntr(USF)=0,0
Exp/Cntr=0.3,0.1

Type RM Length L Ch R = 1 ,3040    ,305.4,302.9,291.3
XS GIS Cut Line= 2
2291627.40857508500682.6489706612291133.12071825500943.406759541
#Sta/Elev= 30
       0 2497.48      22 2494.66    35.3 2492.32    42.8 2490.43    63.5 2482.29
    91.1 2469.16   103.2 2465.26   116.7 2464.53   170.1 2464.34   185.4 2464.71
   238.2 2464.23   261.4 2462.38   270.7  2463.3   277.22461.973   285.5 2461.54
   291.4 2461.98   297.4 2463.28   302.1  2463.6   320.2 2462.55   329.3 2464.59
   338.3 2464.91   350.7 2464.48   424.2 2464.29   455.9 2464.97     483 2466.11
   537.2 2469.65   541.8  2470.4   546.1 2471.88   554.9 2476.59   558.9 2477.46
#Mann= 5 ,-1,0
       0      .1       0     170     .08       0   277.2    .045       0
   291.4     .08       0     500     .06       0
Bank Sta=277.2,291.4
XS Rating Curve= 0 ,0
Exp/Cntr(USF)=0,0
Exp/Cntr=0.3,0.1

Type RM Length L Ch R = 1 ,2737    ,300.3,311.9,332.3
XS GIS Cut Line= 3
2291523.73379155500551.7464662032291184.43449999500614.579668343
2291053.53199554500807.268154905
#Sta/Elev= 30
       0 2487.25     7.7 2486.12    14.6 2484.18    44.3 2472.62    52.4 2468.96
    64.6  2465.2    68.7 2464.61   101.3 2463.71     207 2462.57   292.4 2462.87
   300.6 2462.04   312.8 2461.87     325 2460.96   347.1 2461.88   396.6 2462.63
   406.2    2462   415.9 2462.34     422 2460.67   430.4 2460.22   439.3 2460.74
   450.8 2461.15   465.2 2463.63   473.7 2464.24   517.5 2464.97   537.2 2466.18
   544.8 2467.95   559.1 2474.47   563.1 2475.66   566.2 2476.23     578 2476.62
#Mann= 5 ,-1,0
       0      .1       0     290     .08       0     422    .045       0
   439.3     .08       0  515.07     .06       0
Bank Sta=422,439.3
XS Rating Curve= 0 ,0
Exp/Cntr(USF)=0,0
Exp/Cntr=0.3,0.1

Type RM Length L Ch R = 1 ,2425    ,147.7,149.2,149.5
XS GIS Cut Line= 3
2291543.63097223500542.3214858822291059.81531575500465.874423279
2290910.06285065500517.188205026
#Sta/Elev= 30
       0 2488.38    11.6 2487.16    19.7 2485.81    35.9 2481.19    56.1 2473.57
      74 2469.09    88.5 2466.96   116.9 2465.07   213.8 2462.88   242.4 2461.68
   274.8 2461.42   307.2 2462.29   311.3 2461.47   314.9 2459.67   319.4 2458.65
   323.4  2458.7   328.1 2459.64   331.5 2460.25   339.6 2460.15   359.9 2461.53
   376.1 2460.69   408.5 2460.56   413.2 2460.75   424.7 2462.27   607.8 2462.93
   612.1 2463.68   624.7  2470.5   630.7  2472.9     637 2473.74   648.1 2473.91
#Mann= 5 ,-1,0
       0      .1       0   314.9    .045       0   328.1      .1       0
     360     .05       0  619.82     .06       0
Bank Sta=314.9,328.1
XS Rating Curve= 0 ,0
Exp/Cntr(USF)=0,0
Exp/Cntr=0.3,0.1

Type RM Length L Ch R = 1 ,2276    ,192.7,185.3,176.6
XS GIS Cut Line= 4
2291417.61221586500322.4481140052291300.86117919500380.523432387
2291011.53974454500331.1272081322290851.55831216500402.283471462
#Sta/Elev= 30
       0 2482.44    23.9 2477.72    74.7 2468.57    86.5 2465.73    95.9 2462.32
    99.9 2461.36   150.3 2460.72   179.8 2458.91   183.8    2459   187.9 2459.93
   196.3  2460.2   228.5 2460.14   240.7 2459.29   246.22458.424   252.8 2457.74
   262.1 2458.46   269.1 2459.56   285.3 2459.08   297.5 2460.95   305.6 2461.26
   354.3  2461.7   386.7 2461.41   423.3 2461.95   491.6 2464.67   563.3 2465.43
   567.7 2466.14   576.4 2470.45   580.8 2471.92   586.4 2472.54     599 2472.72
#Mann= 4 ,-1,0
       0      .1       0   246.2    .045       0   262.1     .05       0
  553.91     .06       0
Bank Sta=246.2,262.1
XS Rating Curve= 0 ,0
Exp/Cntr(USF)=0,0
Exp/Cntr=0.3,0.1

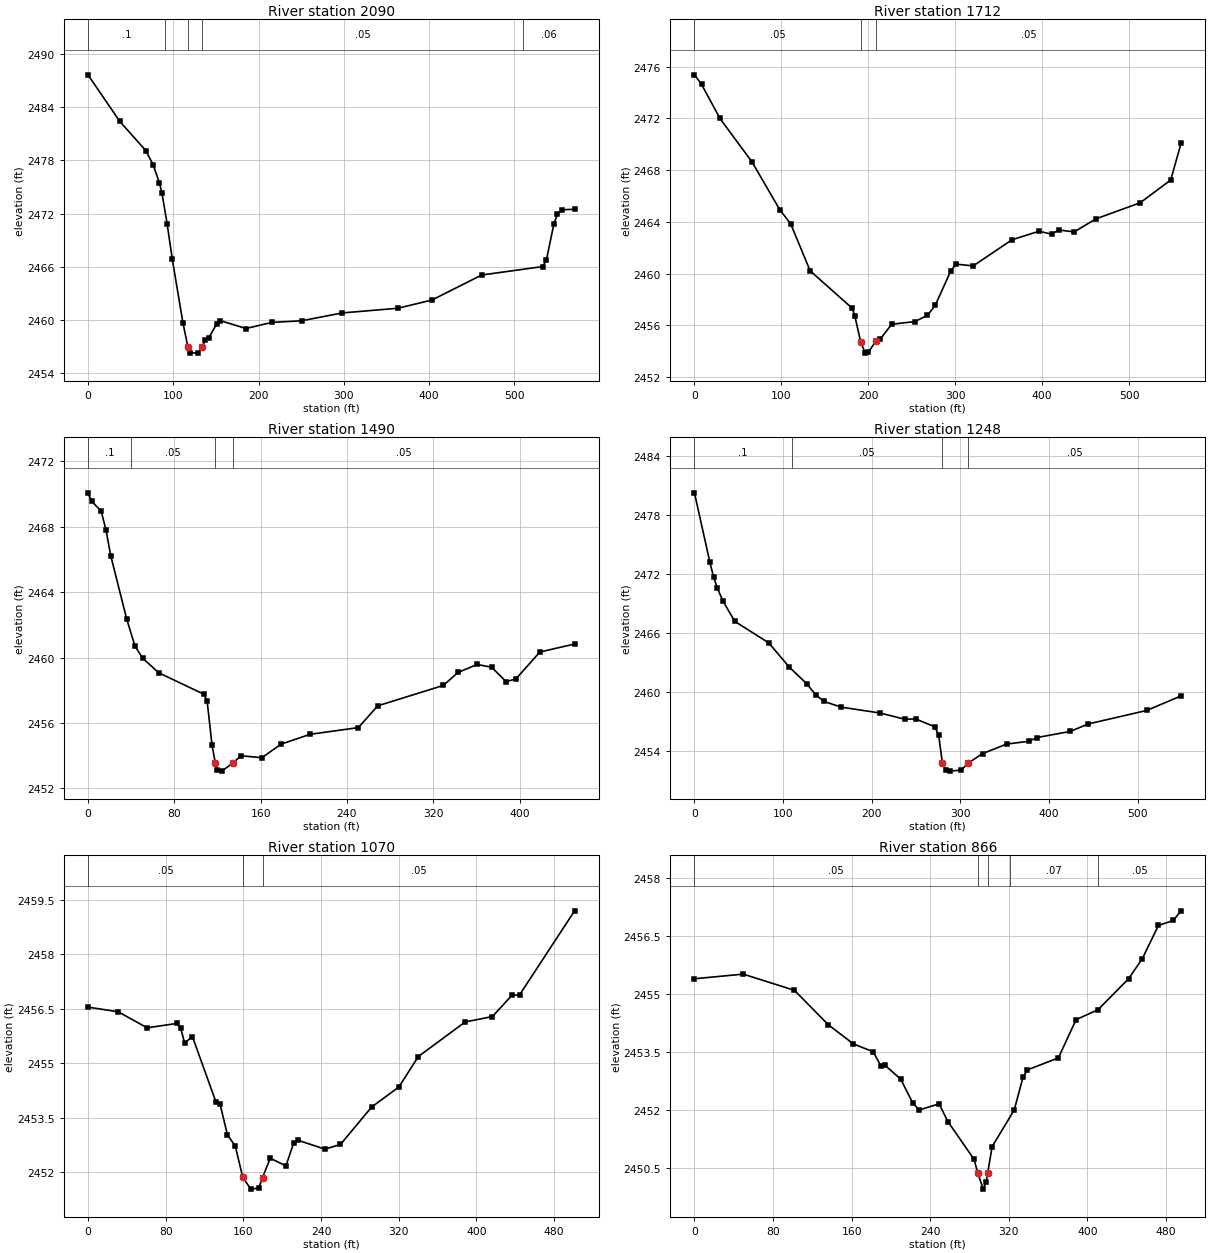
Type RM Length L Ch R = 1 ,2090    ,378,377.8,376.4
XS GIS Cut Line= 2
2291362.50976849500157.7168913492290837.73617284500382.287410108
#Sta/Elev= 30
       0 2487.66    37.3  2482.4    67.8 2479.11    76.5 2477.49    83.6  2475.5
    86.7 2474.32    92.8 2470.86    98.9 2466.83   111.3 2459.69   117.2 2456.93
     120 2456.29   128.7 2456.24   134.32456.923   137.4 2457.73   141.8 2457.97
   151.1 2459.58   154.8 2459.92   185.3 2459.02   215.7 2459.71   250.5 2459.89
   298.4 2460.78   363.7 2461.31   403.6 2462.24   461.8 2465.06   533.3 2466.01
   537.7 2466.76   546.4 2470.78   550.7 2471.96   555.9 2472.43   570.8 2472.48
#Mann= 5 ,-1,0
       0      .1       0      90     .05       0   117.2    .045       0
   134.3     .05       0     510     .06       0
Bank Sta=117.2,134.3
XS Rating Curve= 0 ,0
Exp/Cntr(USF)=0,0
Exp/Cntr=0.3,0.1

Type RM Length L Ch R = 1 ,1712    ,221.4,222.2,221.6
XS GIS Cut Line= 2
2291219.38969695499833.0786802942290717.88765765500082.084333218
#Sta/Elev= 30
       0 2475.36     8.1 2474.63    29.3 2471.99    66.1 2468.64      98 2464.95
   110.8 2463.83   133.1 2460.21   181.5 2457.32   184.5 2456.72   191.2 2454.74
   196.4 2453.85   200.1 2453.91     209 2454.81   213.5 2454.91   226.9 2456.08
   253.7 2456.29   268.1 2456.77     277 2457.54   294.9  2460.2   300.9 2460.73
   320.7 2460.59   365.3 2462.61   396.4 2463.27   411.3 2463.04   418.9 2463.37
   436.8 2463.22     462 2464.23   512.8 2465.47     548 2467.23   559.9 2470.08
#Mann= 3 ,-1,0
       0     .05       0   191.2    .045       0     209     .05       0
Bank Sta=191.2,209
XS Rating Curve= 0 ,0
Exp/Cntr(USF)=0,0
Exp/Cntr=0.3,0.1

Type RM Length L Ch R = 1 ,1490    ,250.9,242.4,223.8
XS GIS Cut Line= 2
2291127.08907274499664.1213391592290723.32291579499865.156169406
#Sta/Elev= 30
       0 2470.07     3.3 2469.56    12.2 2468.95    16.7 2467.79    21.1 2466.22
    35.8 2462.37    43.5 2460.71    50.7 2459.96    65.6 2459.07   107.4 2457.76
   110.4 2457.35     115 2454.63     1182453.554   119.4 2453.15   123.9 2453.06
   134.2 2453.55   141.8    2454   161.1 2453.88     179 2454.71   205.8 2455.31
   250.6 2455.72   268.5 2457.05   329.4  2458.3   342.9 2459.09   360.7 2459.58
   374.1 2459.41   387.5 2458.53   396.5 2458.69   418.8 2460.34     451 2460.83
#Mann= 4 ,-1,0
       0      .1       0      40     .05       0     118    .045       0
   134.2     .05       0
Bank Sta=118,134.2
XS Rating Curve= 0 ,0
Exp/Cntr(USF)=0,0
Exp/Cntr=0.3,0.1

Type RM Length L Ch R = 1 ,1248    ,182.5,178.1,176.1
XS GIS Cut Line= 3
 2291026.1475335499362.9932179042290896.36555448499448.666289022
2290759.79758963499817.654268588
#Sta/Elev= 30
       0 2480.27    17.4 2473.21    21.5 2471.75    25.7 2470.61    31.9 2469.32
    45.5 2467.21    83.8 2465.03   106.9 2462.57     127 2460.85   136.6 2459.76
   146.2 2459.08   165.4  2458.5     209 2457.91     237 2457.28   249.9 2457.29
   271.2  2456.5   275.5 2455.65   279.7 2452.85   283.7 2452.14   288.3    2452
   301.1 2452.11   308.6 2452.81   325.3 2453.79   352.2 2454.75   377.1 2455.03
   386.4 2455.41   423.8 2456.03   444.2 2456.79   510.1 2458.16     549 2459.64
#Mann= 4 ,-1,0
       0      .1       0     110     .05       0   279.7    .045       0
   308.6     .05       0
Bank Sta=279.7,308.6
XS Rating Curve= 0 ,0
Exp/Cntr(USF)=0,0
Exp/Cntr=0.3,0.1

Type RM Length L Ch R = 1 ,1070    ,212.1,203.2,193.7
XS GIS Cut Line= 3
2290710.59919236499318.0360617732290689.39298663499581.841260957
2290706.35795121499817.654268588
#Sta/Elev= 30
       0 2456.54    31.2 2456.41    60.9 2455.97    91.4 2456.09    95.4 2455.96
    99.5 2455.55   107.5 2455.73   131.6 2453.94   136.1 2453.86   143.6 2453.02
   151.6 2452.72   159.42451.854   167.7 2451.53   175.7 2451.56   179.7 2451.84
   179.7 2451.85   187.7 2452.38   203.8 2452.17   211.8  2452.8   215.8 2452.88
   243.9 2452.63     260 2452.76   292.1 2453.79   320.1 2454.34   340.2 2455.18
   388.3 2456.13   416.4 2456.28   436.4 2456.86   444.5 2456.88   501.1 2459.19
#Mann= 3 ,-1,0
       0     .05       0   159.4    .045       0   179.7     .05       0
Bank Sta=159.4,179.7
XS Rating Curve= 0 ,0
Exp/Cntr(USF)=0,0
Exp/Cntr=0.3,0.1

Type RM Length L Ch R = 1 ,866     ,181.1,190.4,182.1
XS GIS Cut Line= 3
2290524.83283023499315.4913170862290514.65385148499536.035856597
2290640.19458936499780.331346517
#Sta/Elev= 30
       0 2455.39    49.7 2455.51   101.8 2455.09   136.2  2454.2   161.9  2453.7
   181.9  2453.5   189.8 2453.13   193.9 2453.15   209.9 2452.79   222.1 2452.18
   228.7 2451.99     249 2452.15     258 2451.69   284.7 2450.71   288.42450.355
     294 2449.94     297 2450.13   298.5 2450.35     303 2451.04   325.5 2451.99
   334.5 2452.84     339 2453.03   370.5 2453.34   388.5 2454.33   410.9 2454.59
   441.9 2455.39   455.9 2455.91   472.3 2456.77   487.4  2456.9   495.4 2457.15
#Mann= 5 ,-1,0
       0     .05       0   288.4    .045       0   298.5     .05       0
  320.78     .07       0  410.78     .05       0
Bank Sta=288.4,298.5
XS Rating Curve= 0 ,0
Exp/Cntr(USF)=0,0
Exp/Cntr=0.3,0.1

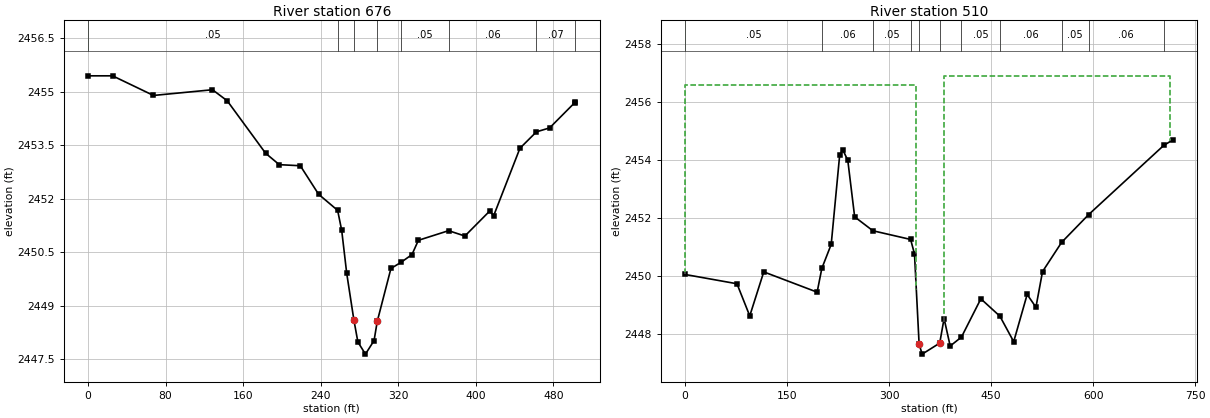
Type RM Length L Ch R = 1 ,676     ,178.4,166.2,153.9
BEGIN DESCRIPTION:
structure xs 4
END DESCRIPTION:
XS GIS Cut Line= 4
2290505.83122165499300.864124627 2290405.7641729499499.893948839
2290386.05566309499566.2418072262290529.58895805499720.724095225
#Sta/Elev= 30
       0 2455.45    25.3 2455.45    67.5  2454.9   128.4 2455.06   143.6 2454.75
   183.2 2453.28   197.3 2452.96     219 2452.93   237.9 2452.13   257.5 2451.68
   261.7 2451.12   266.9 2449.91   274.2 2448.62   278.4 2447.99   286.2 2447.65
   295.1 2448.03   298.4 2448.57   312.5 2450.05   323.3 2450.23   334.2 2450.44
   340.8 2450.84     372 2451.11   388.8 2450.96   414.4 2451.66   418.5 2451.53
   445.6 2453.42   462.6 2453.88   476.2 2453.99   502.2  2454.7   502.9 2454.72
#Mann= 8 ,-1,0
       0     .05       0   257.5     .06       0   274.2    .045       0
   298.4     .06       0   323.3     .05       0     372     .06       0
   462.6     .07       0   502.2     .06       0
Bank Sta=274.2,298.4
XS Rating Curve= 0 ,0
Exp/Cntr(USF)=0,0
Exp/Cntr=0.5,0.3

Type RM Length L Ch R = 1 ,510     ,103.7,105.6,106.2
BEGIN DESCRIPTION:
structure xs 3
END DESCRIPTION:
XS GIS Cut Line= 6
2290123.39837201499137.1819439922290181.24882673499361.664745492
 2290255.7849596499427.1317253172290294.32783694499466.080317154
2290342.37851153499526.2947550472290513.62097898499713.880138375
#Sta/Elev= 30
       0 2450.04    76.2 2449.72      95 2448.61   115.6 2450.13   194.1 2449.43
     201 2450.25   214.8 2451.08   227.2 2454.15   231.8 2454.35   239.2 2453.98
   249.3 2452.03   276.1 2451.55   331.6 2451.25   337.3 2450.75   344.1 2447.63
   348.6 2447.29 374.4082447.671   380.8 2448.52   389.8 2447.57   406.4 2447.88
   434.9  2449.2   462.9  2448.6   483.2 2447.72     503 2449.35   515.9 2448.91
   525.6 2450.14   553.7 2451.15   593.5 2452.11     704  2454.5   716.9 2454.68
#Mann= 11 ,-1,0
       0     .05       0     201     .06       0   276.1     .05       0
   331.6     .07       0   344.1    .045       0 374.408     .07       0
   406.4     .05       0   462.9     .06       0   553.7     .05       0
   593.5     .06       0     704     .07       0
#XS Ineff= 2 ,-1
       0     340  2456.6     380   713.7  2456.9
Permanent Ineff=
       F       F
Bank Sta=344.1,374.408
XS Rating Curve= 0 ,0
Exp/Cntr(USF)=0,0
Exp/Cntr=0.5,0.3