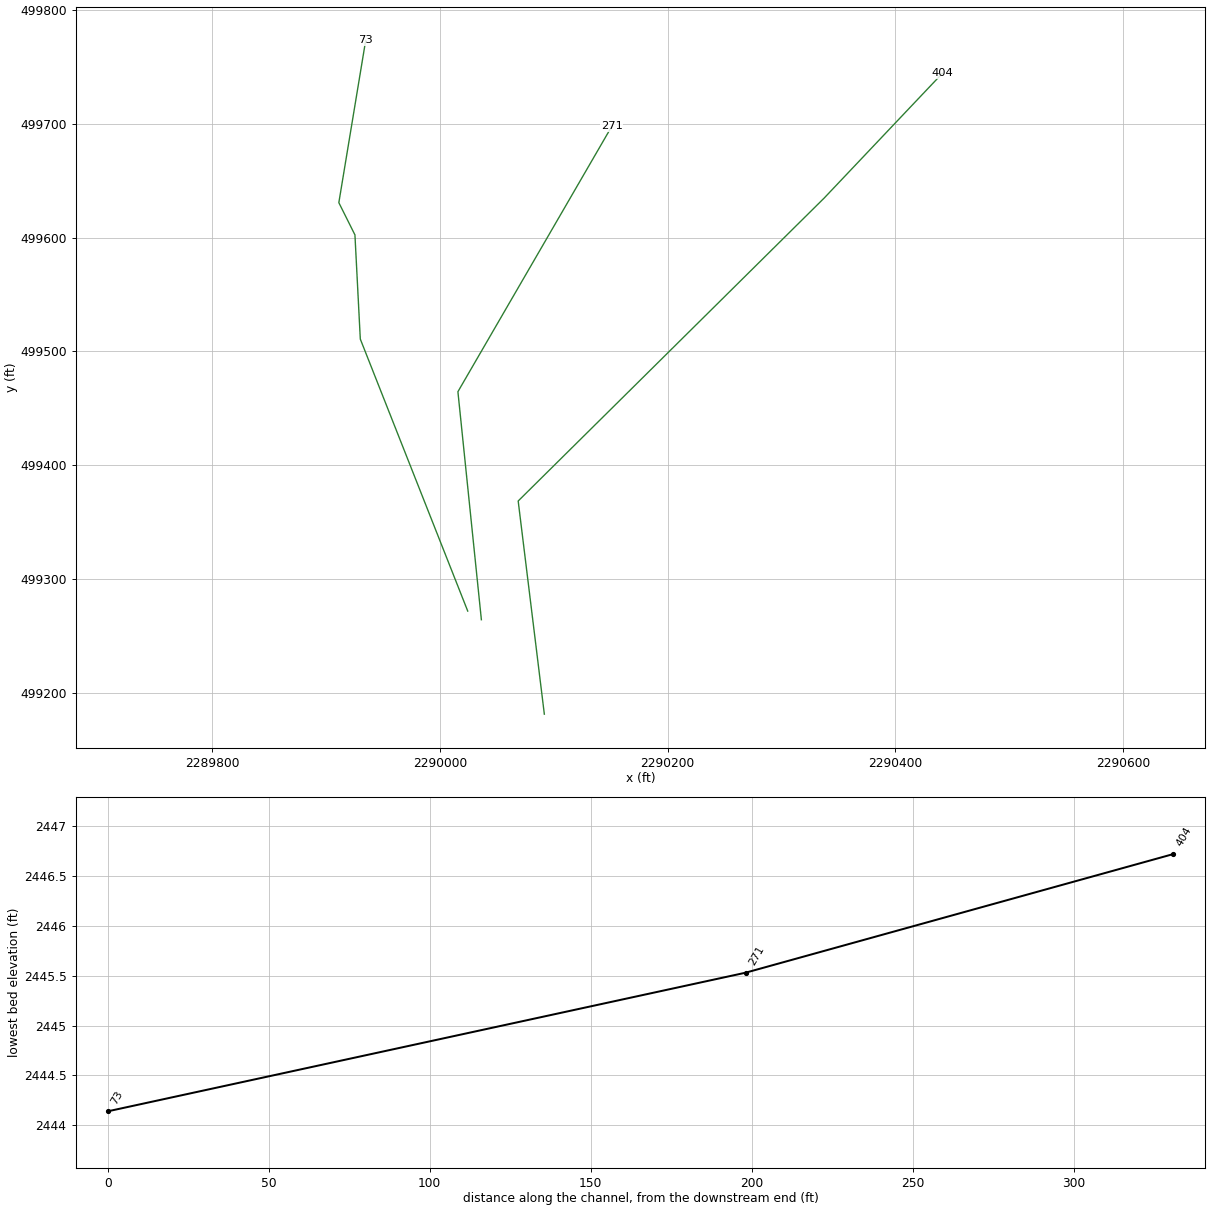
HEC-RAS study MOORERN1.prj: MOORERN1

--- MOORERN1.g01 (geometry) --- (continued)

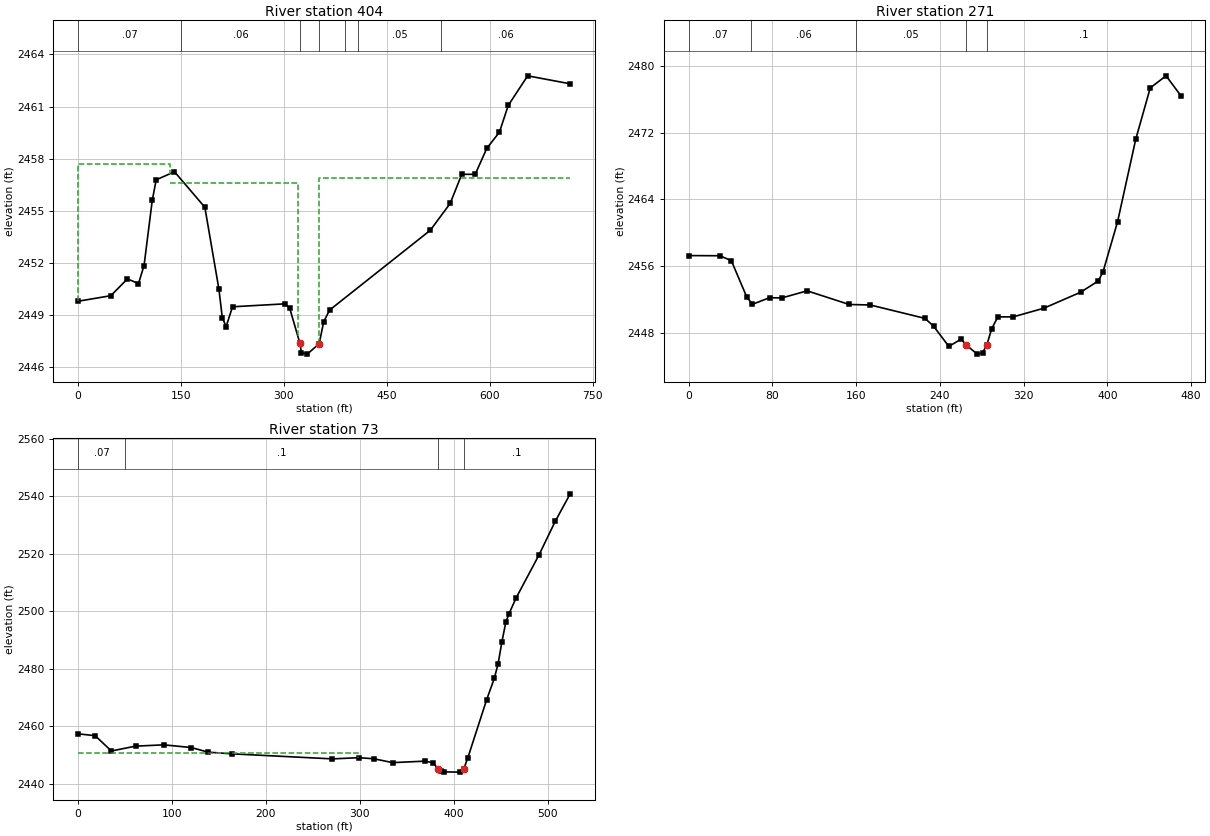
Type RM Length L Ch R = 1 ,404     ,129.1,132.9,140
BEGIN DESCRIPTION:
structure xs 2
END DESCRIPTION:
XS GIS Cut Line= 4
2290091.69922135499181.7411784582290068.73614594499368.798910391
2290337.38308617 499634.61835653 2290441.0578697499743.948128254
#Sta/Elev= 30
       0 2449.77    47.8 2450.09      72 2451.06    88.1 2450.79    96.2 2451.83
   108.2  2455.6   113.9 2456.77   140.5 2457.24   184.8 2455.19   205.3 2450.46
   210.2 2448.82   215.8 2448.31   225.1 2449.45   301.5 2449.62   308.4 2449.37
323.24892447.348   325.5 2446.81     334 2446.72351.34892447.322     358 2448.59
   366.5 2449.26   513.2 2453.86   542.2 2455.41   559.1 2457.09   578.7 2457.09
   595.6 2458.59     614 2459.52   626.8 2461.06   655.1 2462.77   717.1 2462.31
#Mann= 7 ,-1,0
       0     .07       0     150     .06       0323.2489    .045       0
351.3489     .06       0  388.46     .07       0  408.46     .05       0
  528.46     .06       0
#XS Ineff= 3 ,-1
       0  134.19 2457.67  134.19   320.7  2456.6   351.4   717.1  2456.9
Permanent Ineff=
       F       F       F
Bank Sta=323.2489,351.3489
XS Rating Curve= 0 ,0
Exp/Cntr(USF)=0,0
Exp/Cntr=0.5,0.3

Type RM Length L Ch R = 1 ,271     ,198.1,198.1,198.1
XS GIS Cut Line= 3
2290036.42424884499264.6069890112290015.81600229499464.702380719
2290150.84848975  499697.4179442
#Sta/Elev= 30
       0  2457.3    29.9 2457.28    40.8 2456.69    55.4 2452.39    60.9 2451.48
    77.3 2452.27      89 2452.24   113.2 2453.09   153.4 2451.46   173.5  2451.4
   225.8  2449.8     234 2448.87   248.6 2446.45   260.3 2447.32  265.282446.614
   275.7 2445.53   280.8 2445.69  284.95 2446.66   289.5 2448.55   295.4 2449.98
     310 2449.98   339.3 2451.01   374.4 2452.92   391.3 2454.26   395.9 2455.36
   409.8 2461.35   427.1 2471.17     441 2477.33   456.1 2478.77   470.2 2476.41
#Mann= 5 ,-1,0
       0     .07       0      60     .06       0     160     .05       0
  265.28    .045       0  284.95      .1       0
Bank Sta=265.28,284.95
XS Rating Curve= 0 ,0
Exp/Cntr(USF)=0,0
Exp/Cntr=0.3,0.1

Type RM Length L Ch R = 1 ,73      ,,,
XS GIS Cut Line= 5
2290024.43509724499272.2092603092289930.11907065499510.880618396
2289925.40658049499602.3029275092289911.26911001499630.577868472
2289934.83156081499772.895071319
#Sta/Elev= 30
       0 2457.45    18.2 2456.81    35.5 2451.49    61.3 2453.17    91.4 2453.62
   120.4 2452.69   138.7 2451.07     164  2450.5   270.9 2448.74     299 2449.16
     315 2448.78     335 2447.44   369.3 2447.96   378.2 2447.43   382.8 2445.37
   386.3 2444.43   389.8 2444.22   406.8 2444.14   410.8 2445.35   414.9    2449
   435.1 2469.36   443.2 2476.73   447.3 2481.87   451.3 2489.42   455.4 2496.15
   458.8 2499.16   466.3 2504.59   490.7 2519.56   508.1 2531.31     524 2540.85
#Mann= 4 ,-1,0
       0     .07       0      50      .1       0   382.8    .045       0
   410.8      .1       0
#XS Ineff= 2 , 0
          298.45 2450.67
Permanent Ineff=
       F       F
Bank Sta=382.8,410.8
XS Rating Curve= 0 ,0
Exp/Cntr(USF)=0,0
Exp/Cntr=0.3,0.1
LCMann Table=0

Chan Stop Cuts=-1
Use User Specified Reach Order=0
Composite Channel Slope=5